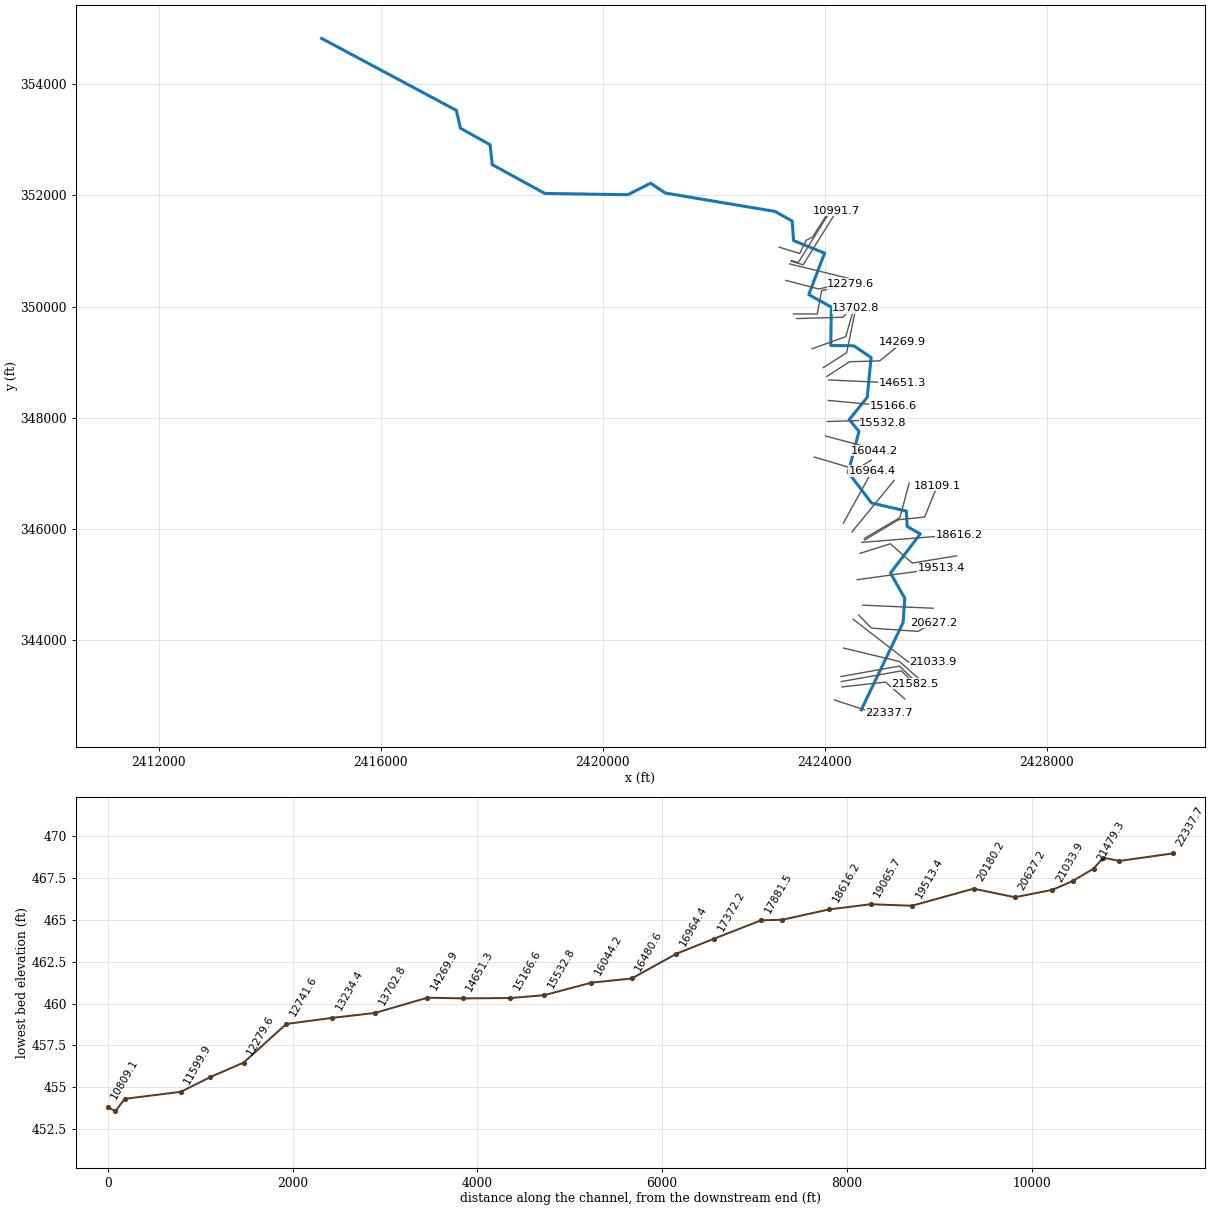
--- OPQNTRIB2.prj (project) ---

Proj Title=OPQNTRIB2
Current Plan=p01
Default Exp/Contr=0,0
English Units
Geom File=g01
Flow File=f01
Plan File=p01
BEGIN DESCRIPTION:
END DESCRIPTION:
DSS Export Rating Curves= 0
DSS Export Rating Curve Sorted= 0
DSS Export Volume Flow Curves= 0
DXF OffsetX= 0
DXF OffsetY= 0
DXF ScaleX= 0
DXF ScaleY= 0

--- OPQNTRIB2.p01 (plan) ---

Plan Title=Floodplain
Program Version=4.00
Geom File=g01
Flow File=f01
K Sum by GR=0
Std Step Tol=0.01
Critical Tol=0.01
Num of Std Step Trials=20
Max Error Tol=0.3
Flow Tol Ratio=0.001
Split Flow NTrial=30
Split Flow Tol=0.02
Split Flow Ratio=0.02
Log Output Level=0
Friction Slope Method=1
Unsteady Friction Slope Method=2
Unsteady Bridges Friction Slope Method=1
Global Log Level=0
CheckData=False
Run HTab=0
Run UNet=0
Run PostProcess=0
UNET Theta=0
UNET Theta Warmup=0
UNET ZTol=0
UNET ZSATol=0
UNET MxIter=0
UNET MaxInSteps=0
UNET DtIC=0
UNET DtMin=0
UNET MaxCRTS=0
UNET WFStab=0
UNET SFStab=0
UNET WFX=0
UNET SFX=0
UNET DSS MLevel=0
UNET DZMax Abort=0
UNET Convert EG Bridges=0
UNET Use Existing IB Tables=0
UNET Froude Limit=0
UNET Froude Power=0
Write IC File=0
Echo Input=False
Echo Output=False
Write Detailed=0

--- OPQNTRIB2.f01 (steady flow) ---

Flow Title=NFF Regression Equation
Program Version=4.10
Number of Profiles= 1
Profile Names=P100yr
River Rch & RM=OPQNTRIB2,Main            ,22337.7
554.8052
River Rch & RM=OPQNTRIB2,Main            ,21253.1
600.4815
River Rch & RM=OPQNTRIB2,Main            ,19065.7
660.7347
River Rch & RM=OPQNTRIB2,Main            ,18616.2
718.5204
River Rch & RM=OPQNTRIB2,Main            ,16480.6
 794.958
River Rch & RM=OPQNTRIB2,Main            ,13702.8
854.9154
River Rch & RM=OPQNTRIB2,Main            ,10991.7
 942.653
River Rch & RM=OPQNTRIB2,Main            ,9698
975.0968
River Rch & RM=OPQNTRIB2,Main            ,7146
1082.097
River Rch & RM=OPQNTRIB2,Main            ,6211.3
1189.949
River Rch & RM=OPQNTRIB2,Main            ,3542.8
1255.568
River Rch & RM=OPQNTRIB2,Main            ,245.9
1369.639
River Rch & RM=OPQNTRIB2,Main            ,245.9
1368.982
Boundary for River Rch & Prof#=OPQNTRIB2,Main            , 1
Up Type= 0
Dn Type= 3
Dn Slope=0.008845
DSS Import GetInterval= 0
DSS Import GetPeak= 0
DSS Import FillOption= 0

--- OPQNTRIB2.g01 (geometry) ---

Geom Title=USGS 10m DEM
Program Version=4.10

River Reach=OPQNTRIB2       ,Main
Reach XY= 30
     2424657.114      342741.352     2425410.586      344312.532
       2425440.1      344750.032     2425183.156      345203.157
     2425719.614      345908.018     2425483.503      346041.699
      2425468.31      346319.336     2424841.142      346463.574
     2424422.739      347015.657     2424615.447      347753.504
     2424440.409      347965.432     2424764.753      348368.088
     2424833.329      349082.715        2424523.      349294.303
     2424107.418      349299.728     2424117.183      349990.917
     2423711.367      350215.527     2423995.656       350963.14
     2423437.134      351187.966     2423412.178      351540.614
     2423102.933       351713.14     2421127.401      352043.945
     2420860.474      352220.811     2420450.041       352013.46
     2418955.092      352037.434     2418008.912      352555.013
     2417969.849      352913.085     2417435.995       353211.48
     2417361.722       353532.28     2414933.481      354829.173

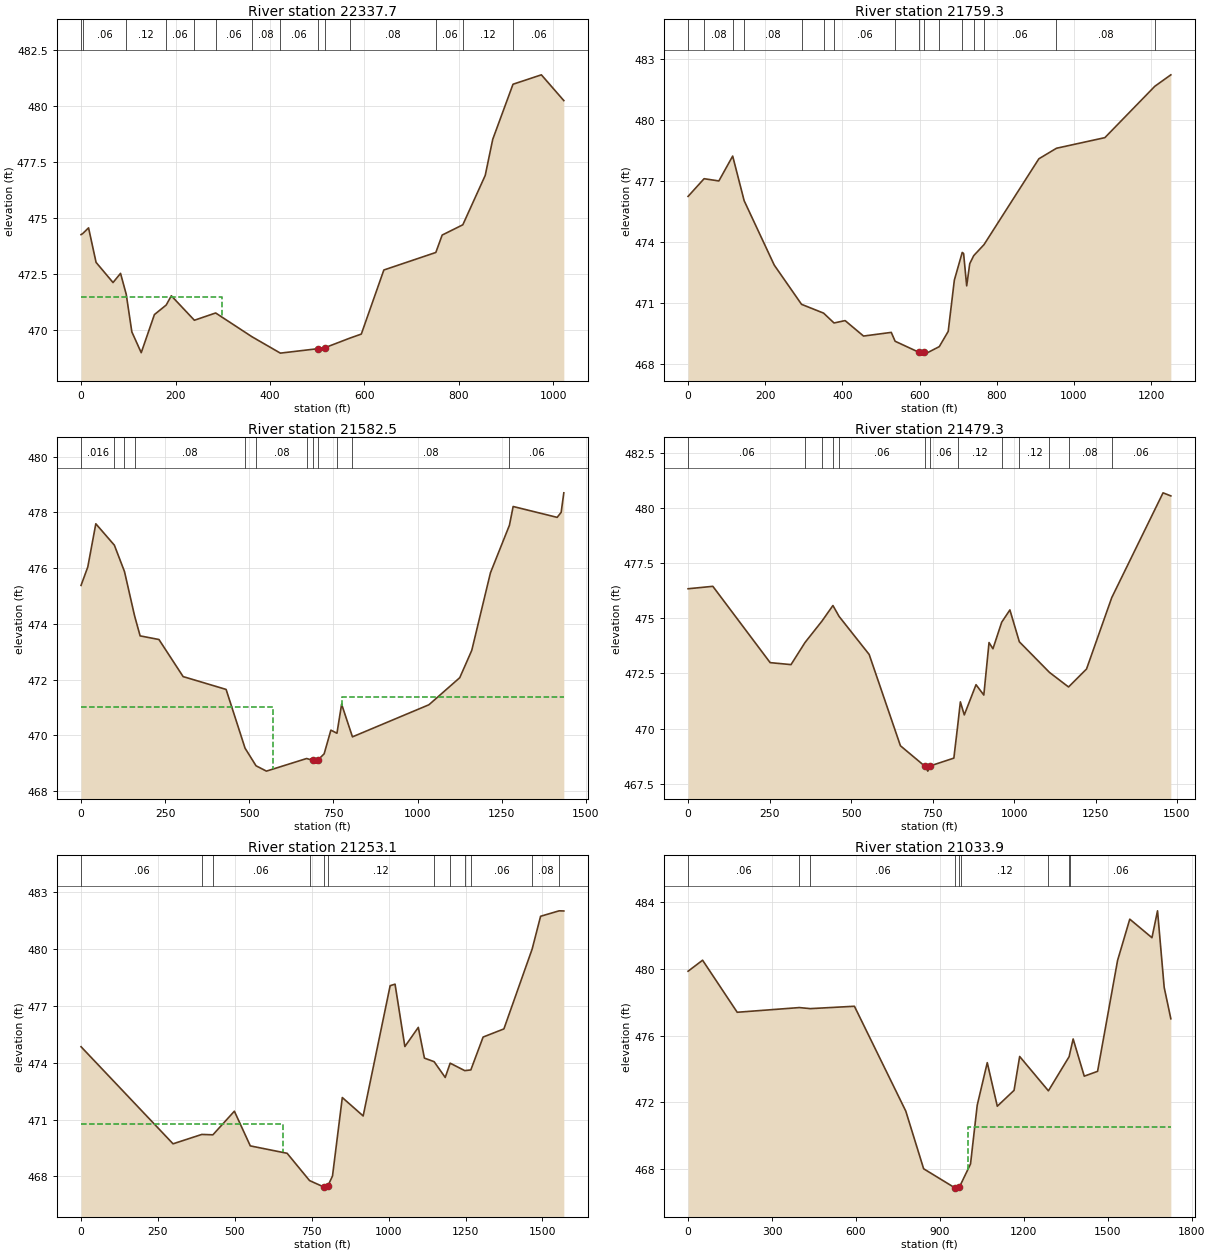
Type RM Length L Ch R = 1 ,22337.7 ,568.4,578.4,588.4
XS GIS Cut Line= 3
     2424174.493      342917.984      2424908.29      342676.755
     2425157.856      342681.096
#Sta/Elev= 30
       0  474.27    3.28 474.311    15.9  474.57    31.8  473.03    67.7  472.13
    83.6  472.54   95.63471.6069   107.5  469.93   127.4     469   155.3   470.7
  180.24 471.126   191.1  471.54  239.92470.4474  284.95470.7719  361.57469.7146
  421.76468.9818     422  468.98   502.2  469.18   517.2  469.23  569.69469.6544
   593.3  469.83     641  472.69  751.06473.4724   764.5  474.25  808.19474.7072
   855.6  476.91   871.5  478.52  914.42480.9796   974.5   481.4    1022  480.25
#Mann= 14 ,-1 , 0
       0     .12       0    3.28     .06       0   95.63     .12       0
  180.24     .06       0  239.92     .08       0  284.95     .06       0
  361.57     .08       0  421.76     .06       0   502.2    .045       0
   517.2     .06       0  569.69     .08       0  751.06     .06       0
  808.19     .12       0  914.42     .06       0
#XS Ineff= 2 , 0
          298.45   471.5
Permanent Ineff=
       F       F
Bank Sta=502.2,517.2
XS Rating Curve= 0 ,0
Exp/Cntr=0.3,0.1

Type RM Length L Ch R = 1 ,21759.3 ,175.3,176.8,178.3
XS GIS Cut Line= 3
     2424308.825      343152.793     2425093.981      343240.033
     2425441.637      342936.647
#Sta/Elev= 30
       0  476.24   41.51477.1101    79.8     477  115.61478.2231  145.36476.0272
   223.4  472.86  294.12470.9305  351.21470.4981  378.36470.0132     407  470.13
   454.8  469.37   526.7  469.55  536.67469.1148   597.4  468.58   612.4  468.58
   618.4  468.53  651.15468.8498   674.3   469.6   690.2  472.12  710.65473.4832
   714.2  473.43   722.2  471.84   730.1  472.93   740.4473.3245  767.08 473.867
   909.3  478.09  954.95 478.608  1080.4  479.13 1209.83481.6559  1251.4  482.22
#Mann= 16 ,-1 , 0
       0     .06       0   41.51     .08       0  115.61     .06       0
  145.36     .08       0  294.12     .06       0  351.21     .08       0
  378.36     .06       0  536.67     .08       0   597.4    .045       0
   612.4     .08       0  651.15     .12       0  710.65     .06       0
   740.4     .08       0  767.08     .06       0  954.95     .08       0
 1209.83     .06       0
Bank Sta=597.4,612.4
XS Rating Curve= 0 ,0
Exp/Cntr=0.3,0.1

Type RM Length L Ch R = 1 ,21582.5 ,103.3,103.2,102.7
XS GIS Cut Line= 3
     2424298.408      343249.147     2425379.137      343441.856
     2425622.627      343208.783
#Sta/Elev= 30
       0  475.38      20  476.04    43.9  477.59   99.02476.8229  129.09475.8774
  159.16474.2856   175.6  473.57   231.5  473.44   303.4  472.11   431.1  471.65
  487.36469.5447     520 468.912   550.9  468.72  670.35469.1719   688.9  469.11
   703.9  469.12   722.5  469.34   742.5  470.19  760.56470.0785   774.4  471.12
  806.63469.9489  1033.9   471.1  1125.5  472.07  1161.2  473.05  1216.7  475.83
 1273.19477.5392  1284.2  478.21    1415  477.82  1426.9     478  1434.8   478.7
#Mann= 12 ,-1 , 0
       0    .016       0   99.02     .08       0  129.09     .06       0
  159.16     .08       0  487.36     .06       0     520     .08       0
  670.35     .12       0   688.9    .045       0   703.9     .12       0
  760.56     .06       0  806.63     .08       0 1273.19     .06       0
#XS Ineff= 2 , 0
          569.66  471.02  776.06          471.39
Permanent Ineff=
       F       F
Bank Sta=688.9,703.9
XS Rating Curve= 0 ,0
Exp/Cntr=0.3,0.1

Type RM Length L Ch R = 1 ,21479.3 ,236.2,226.1,216.3
XS GIS Cut Line= 3
     2424290.596      343340.293     2425345.283      343527.793
     2425642.158      343245.241
#Sta/Elev= 30
       0  476.34      76  476.45   251.8  472.99   315.8   472.9  358.76 473.903
  410.45474.8675  444.39475.5803  463.36475.0836   555.6  473.36   651.5  469.22
   727.5  468.28   735.5  468.07   743.5  468.31   815.4  468.66  826.83470.0874
   835.4  471.21   847.4  470.62   883.4  471.99   907.3  471.52   923.3   473.9
   935.3  473.62  962.18474.8232   987.3  475.38 1016.33473.9348 1108.72472.5471
 1167.21471.8864  1222.4   472.7 1299.77475.9375  1457.2  480.69  1481.1  480.55
#Mann= 13 ,-1 , 0
       0     .06       0  358.76    .016       0  410.45     .06       0
  444.39     .08       0  463.36     .06       0   727.5    .045       0
   743.5     .06       0  826.83     .12       0  962.18     .06       0
 1016.33     .12       0 1108.72    .016       0 1167.21     .08       0
 1299.77     .06       0
Bank Sta=727.5,743.5
XS Rating Curve= 0 ,0
Exp/Cntr=0.3,0.1

Type RM Length L Ch R = 1 ,21253.1 ,229.1,219.3,209.2
XS GIS Cut Line= 3
     2424339.858      343851.578     2425344.487      343611.651
     2425745.023      343254.356
#Sta/Elev= 30
       0  474.84   299.1  469.72  392.59470.2145  428.63470.1945   498.5  471.44
   550.3  469.61     670  469.22  742.91467.7811   789.6  467.44   797.6  467.33
   801.6  467.47   817.5  468.02   849.4  472.16   917.2  471.19    1005  478.06
  1020.9  478.14  1052.8  474.85  1096.5  475.86  1116.4  474.24 1147.87474.0524
    1184  473.22  1200.1473.9726 1247.63473.5792 1267.29473.6174  1307.2  475.35
  1374.8  475.78 1466.71479.9957  1494.1  481.72  1554.3482.0075  1569.6     482
#Mann= 12 ,-1 , 0
       0     .06       0  392.59    .016       0  428.63     .06       0
  742.91     .12       0   789.6    .045       0   801.6     .12       0
 1147.87     .06       0  1200.1    .016       0 1247.63     .08       0
 1267.29     .06       0 1466.71     .08       0  1554.3     .06       0
#XS Ineff= 2 , 0
          655.52  470.74
Permanent Ineff=
       F       F
Bank Sta=789.6,801.6
XS Rating Curve= 0 ,0
Exp/Cntr=0.3,0.1

Type RM Length L Ch R = 1 ,21033.9 ,392.9,406.7,420.9
XS GIS Cut Line= 3
      2424510.07      344371.125     2425565.147       343556.79
     2425954.398      343609.217
#Sta/Elev= 30
       0  479.86    51.9  480.52   175.6   477.4  397.78477.6814  436.78477.6183
   594.6  477.76   778.1  471.48     842  468.02  952.47466.8892   957.7   466.8
   969.7   466.9  975.02 467.104  1009.6  468.31  1033.5  471.83  1069.4  474.38
  1105.3  471.77  1165.2  472.72  1185.2  474.75 1287.97472.6916 1362.14474.7427
 1365.79475.0258  1376.4   475.8  1416.1  473.57  1463.7  473.86  1535.1   480.5
  1578.8  482.98  1658.1  481.87    1678  483.48  1701.8  478.89  1725.6  477.01
#Mann= 9 ,-1 , 0
       0     .06       0  397.78    .016       0  436.78     .06       0
  952.47    .045       0   969.7     .06       0  975.02     .12       0
 1287.97     .06       0 1362.14     .08       0 1365.79     .06       0
#XS Ineff= 2 , 0
                          999.38           470.5
Permanent Ineff=
       F       F
Bank Sta=952.47,969.7
XS Rating Curve= 0 ,0
Exp/Cntr=0.3,0.1

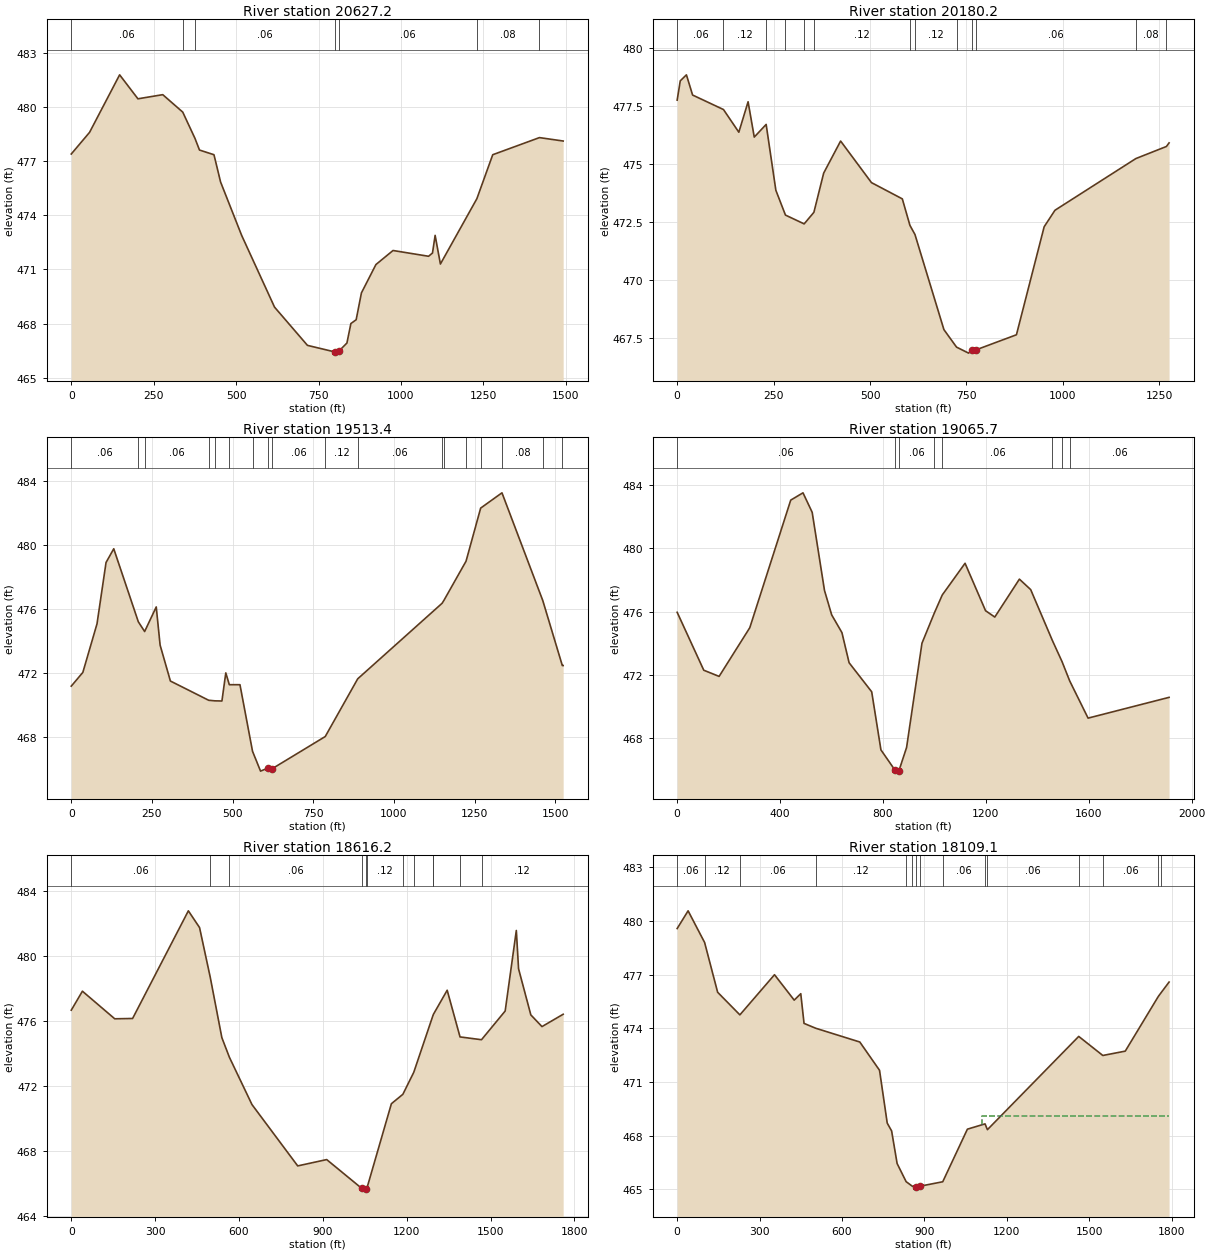
Type RM Length L Ch R = 1 ,20627.2 ,446.1,447,447.3
XS GIS Cut Line= 4
     2424610.084      344447.832     2424839.251      344211.721
     2425679.529      344152.693     2425957.306      344312.415
#Sta/Elev= 30
       0   477.4    55.5   478.6   146.7  481.79   202.2  480.46   277.5  480.69
  338.08479.7233  375.06478.2708   388.9  477.62   432.8  477.36   452.8  475.85
   516.7  472.89   616.5  468.91   716.3  466.79   798.5  466.43   800.1  466.36
   812.1  466.48     836  466.92     848     468     864  468.21     880   469.7
   923.9  471.27   975.8  472.05  1083.6  471.73  1095.5  471.91  1103.5  472.89
  1119.5   471.3 1230.09474.9225  1278.2  477.36 1419.87478.3091  1491.8  478.12
#Mann= 7 ,-1 , 0
       0     .06       0  338.08    .016       0  375.06     .06       0
   798.5    .045       0   812.1     .06       0 1230.09     .08       0
 1419.87     .06       0
Bank Sta=798.5,812.1
XS Rating Curve= 0 ,0
Exp/Cntr=0.3,0.1

Type RM Length L Ch R = 1 ,20180.2 ,661.7,666.8,669.1
XS GIS Cut Line= 2
     2424679.529      344624.915     2425953.834       344569.36
#Sta/Elev= 30
       0  477.76       8  478.59      24  478.85      40  477.98   120.1477.3555
   159.9  476.38   183.9  477.69   199.9  476.17  230.73476.7148   255.9  473.88
  280.78472.8126  329.26472.4334  354.48472.9303   379.9  474.62   423.8     476
   503.8  474.21   583.8  473.51  603.54472.3701  616.59471.9764   691.7  467.88
  724.43467.1282   755.7  466.87   763.7     467   774.8  467.01   879.7  467.66
   951.6  472.31   979.6  473.02 1189.39475.2455  1268.6475.7655  1275.5  475.92
#Mann= 13 ,-1 , 0
       0     .06       0   120.1     .12       0  230.73     .06       0
  280.78    .016       0  329.26     .06       0  354.48     .12       0
  603.54     .06       0  616.59     .12       0  724.43     .06       0
   763.7    .045       0   774.8     .06       0 1189.39     .08       0
  1268.6     .06       0
Bank Sta=763.7,774.8
XS Rating Curve= 0 ,0
Exp/Cntr=0.3,0.1

Type RM Length L Ch R = 1 ,19513.4 ,467.1,447.7,430.7
XS GIS Cut Line= 2
     2424582.306      345083.249     2426092.723      345291.582
#Sta/Elev= 30
       0  471.17    35.9  472.03    79.8  475.07   107.8  478.91   131.7  479.77
  207.86475.1993  227.46474.5896   263.4  476.13   275.4  473.74   307.3  471.49
  425.97470.2856  445.25  470.25     467  470.24     479     472  489.89471.2611
   522.9  471.26  561.86467.0927   586.7  465.85   610.7  466.05   622.7     466
  787.22468.0152  887.86471.6276 1149.42476.3576  1155.2476.5438 1223.64 478.992
 1268.96482.3164 1335.02483.2724 1461.54476.5267 1522.04  472.46  1524.7  472.46
#Mann= 18 ,-1 , 0
       0     .06       0  207.86     .12       0  227.46     .06       0
  425.97     .12       0  445.25     .06       0  489.89     .12       0
  561.86     .06       0   610.7    .045       0   622.7     .06       0
  787.22     .12       0  887.86     .06       0 1149.42     .12       0
  1155.2     .06       0 1223.64     .12       0 1268.96     .06       0
 1335.02     .08       0 1461.54     .06       0 1522.04     .12       0
Bank Sta=610.7,622.7
XS Rating Curve= 0 ,0
Exp/Cntr=0.3,0.1

Type RM Length L Ch R = 1 ,19065.7 ,431.6,449.5,467.8
XS GIS Cut Line= 4
     2424634.418      345557.253     2425180.301      345729.986
     2425575.362       345381.86     2426377.445      345513.804
#Sta/Elev= 30
       0  475.95   103.4   472.3     163  471.91   282.3  474.98   441.4  483.02
   489.1  483.48   524.8  482.25   572.6  477.33   600.5  475.79   640.4  474.67
   668.3  472.77   756.1  470.94     792  467.28   847.1  465.99   859.8  465.94
   862.1  465.97   891.7  467.43   951.5     474  999.31475.8955 1030.38477.0416
    1119  479.04  1198.7  476.05  1234.6  475.65  1330.2  478.04  1374.1  477.38
 1458.32474.1768 1495.86472.8452 1525.85471.6203  1597.2  469.28    1912  470.59
#Mann= 8 ,-1 , 0
       0     .06       0   847.1    .045       0   862.1     .06       0
  999.31     .12       0 1030.38     .06       0 1458.32     .12       0
 1495.86     .08       0 1525.85     .06       0
Bank Sta=847.1,862.1
XS Rating Curve= 0 ,0
Exp/Cntr=0.3,0.1

Type RM Length L Ch R = 1 ,18616.2 ,506.7,507.1,506.9
XS GIS Cut Line= 2
       2424664.8       345755.17     2426419.285      345894.547
#Sta/Elev= 30
       0  476.65    39.9  477.82   155.6  476.12   219.5  476.14     419  482.77
     459  481.74  497.16478.6874   538.8  474.96  565.72473.7539   646.5  470.84
   810.2  467.06   913.9  467.45  1039.1  465.68  1049.6  465.63  1054.1  465.66
 1058.12465.7043  1145.4  470.89 1186.48471.4706 1225.39472.8224 1292.85476.2581
 1295.74476.3954    1345  477.88 1390.97475.0044 1467.79474.8318  1552.5   476.6
  1592.4  481.56  1600.4   479.2  1644.3  476.36  1684.2  475.64    1760   476.4
#Mann= 12 ,-1 , 0
       0     .06       0  497.16     .12       0  565.72     .06       0
  1039.1    .045       0  1054.1     .06       0 1058.12     .12       0
 1186.48     .06       0 1225.39     .12       0 1292.85     .06       0
 1295.74     .12       0 1390.97     .08       0 1467.79     .12       0
Bank Sta=1039.1,1054.1
XS Rating Curve= 0 ,0
Exp/Cntr=0.3,0.1

Type RM Length L Ch R = 1 ,18109.1 ,200.2,227.6,255.2
XS GIS Cut Line= 4
     2424717.361      345797.514        2425325.      346162.097
     2425798.047      346211.912     2426027.647      346772.965
#Sta/Elev= 30
       0  479.57    39.8  480.56   99.91478.7897   147.3  476.01  228.27474.7467
   354.3  476.99     426  475.57   449.9  475.93   461.8  474.27  504.24473.9998
   664.8  473.23   736.6  471.65   764.6   468.7   780.6  468.26   800.6  466.44
  833.46465.4262  855.76465.1748   867.6  465.14   876.5  465.01   882.6  465.17
  966.65465.4216  1056.4  468.36 1120.64468.6564 1129.25 468.331 1461.64473.5427
 1549.29472.4778    1631  472.72 1751.41475.7782 1760.22475.9602  1790.5  476.58
#Mann= 15 ,-1 , 0
       0     .06       0   99.91     .12       0  228.27     .06       0
  504.24     .12       0  833.46     .06       0  855.76     .12       0
   867.6    .045       0   882.6     .12       0  966.65     .06       0
 1120.64     .12       0 1129.25     .06       0 1461.64     .12       0
 1549.29     .06       0 1751.41     .12       0 1760.22     .06       0
#XS Ineff= 2 , 0
                         1108.36          469.08
Permanent Ineff=
       F       F
Bank Sta=867.6,882.6
XS Rating Curve= 0 ,0
Exp/Cntr=0.3,0.1

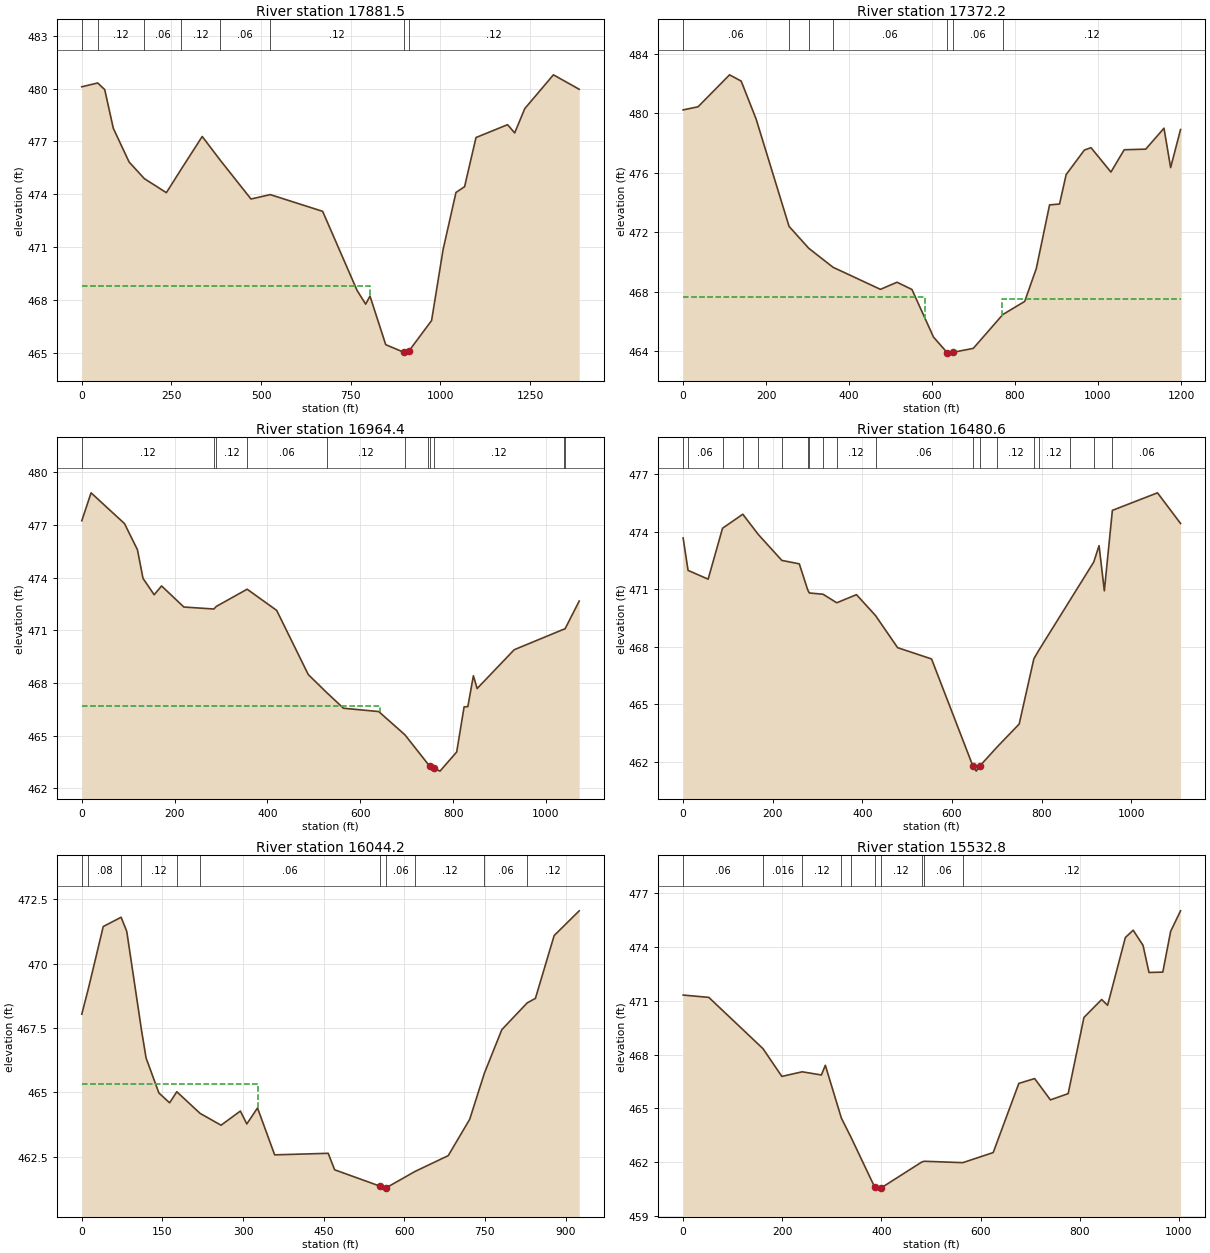
Type RM Length L Ch R = 1 ,17881.5 ,518.8,509.3,499.2
XS GIS Cut Line= 3
     2424710.417      345825.291     2425352.778      346200.291
     2425519.445      346821.819
#Sta/Elev= 30
       0   480.1   44.38480.3176      64  479.94      88  477.74     132  475.83
  174.57 474.885   235.9  474.09  277.52475.4286   335.9  477.28  386.17475.9335
   471.9  473.73  525.77473.9787   671.8  473.03   767.8  468.54   791.8  467.76
   803.8  468.22   847.7  465.46   898.1  465.03   903.7  464.98   911.7  465.08
   975.6  466.83  1007.6  470.85  1043.6   474.1  1067.6  474.43  1099.5  477.22
  1187.5  477.95  1207.4  477.48  1235.4  478.86  1315.4  480.78  1387.3  479.96
#Mann= 8 ,-1 , 0
       0     .06       0   44.38     .12       0  174.57     .06       0
  277.52     .12       0  386.17     .06       0  525.77     .12       0
   898.1    .045       0   911.7     .12       0
#XS Ineff= 2 , 0
          804.75  468.77
Permanent Ineff=
       F       F
Bank Sta=898.1,911.7
XS Rating Curve= 0 ,0
Exp/Cntr=0.3,0.1

Type RM Length L Ch R = 1 ,17372.2 ,403.3,407.7,412.1
XS GIS Cut Line= 2
     2424488.195      345943.347     2425248.611       346870.43
#Sta/Elev= 30
       0  480.24      36  480.45   111.9   482.6   139.9  482.18   175.9  479.63
  255.39472.4046  302.88470.9307  361.32469.6557   475.6  468.17   515.6  468.65
   551.6  468.16   603.5  464.96   636.3  463.92   647.5  463.88   651.3  463.94
   699.4   464.2  770.57466.4747   823.4  467.36   851.3  469.57   883.3  473.85
   907.3  473.91   923.3  475.89   967.2  477.54   983.2   477.7  1031.2  476.06
  1063.2  477.56  1115.1   477.6  1159.1  479.01  1175.1  476.36    1199  478.92
#Mann= 7 ,-1 , 0
       0     .06       0  255.39     .06       0  302.88     .12       0
  361.32     .06       0   636.3    .045       0   651.3     .06       0
  770.57     .12       0
#XS Ineff= 2 , 0
          583.28  467.64   767.8          467.52
Permanent Ineff=
       F       F
Bank Sta=636.3,651.3
XS Rating Curve= 0 ,0
Exp/Cntr=0.3,0.1

Type RM Length L Ch R = 1 ,16964.4 ,516.7,483.9,450.5
XS GIS Cut Line= 2
     2424334.983      346102.346     2424852.435      347040.576
#Sta/Elev= 30
       0  477.23      20  478.82      92  477.07   119.9  475.58   131.9  473.95
   155.9  473.02   171.9  473.52   219.9  472.32  284.57472.2068  289.88 472.356
   356.2 473.334   419.8  472.13   487.8  468.48  528.35467.4321   563.7  466.56
   639.7  466.37   696.1465.0475  745.37463.3967   749.8  463.25   759.6  463.14
   771.6  462.98   807.6  464.07   823.6  466.64   831.6  466.65   843.6  468.41
   851.6  467.68   931.5  469.89 1038.55 471.059 1040.79471.0658  1071.5  472.66
#Mann= 11 ,-1 , 0
       0     .12       0  284.57     .06       0  289.88     .12       0
   356.2     .06       0  528.35     .12       0   696.1     .06       0
  745.37     .12       0   749.8    .045       0   759.6     .12       0
 1038.55     .06       0 1040.79     .12       0
#XS Ineff= 2 , 0
          641.49  466.68
Permanent Ineff=
       F       F
Bank Sta=749.8,759.6
XS Rating Curve= 0 ,0
Exp/Cntr=0.3,0.1

Type RM Length L Ch R = 1 ,16480.6 ,435.8,436.4,436.9
XS GIS Cut Line= 3
     2423807.595      347291.628     2424561.067      347069.116
     2424838.845      347236.217
#Sta/Elev= 30
       0  473.68   11.03 471.987    55.8  471.53   87.95  474.19  133.14474.9223
  167.46473.8717  220.28472.5078   259.2  472.33  277.88470.9758  281.53470.8085
  312.16470.7419  342.78470.2955   386.8  470.72   429.3 469.627   478.6  467.95
   554.3  467.36   646.1  461.79     654   461.5     662  461.77  700.89462.7698
   749.8  463.96  782.48467.3658     793467.7905   863.4  470.44  916.18472.4262
     928  473.28   939.8  470.92  957.71475.1237  1058.4  476.04  1109.8  474.44
#Mann= 19 ,-1 , 0
       0     .12       0   11.03     .06       0   87.95     .08       0
  133.14     .06       0  167.46     .08       0  220.28     .06       0
  277.88     .08       0  281.53    .016       0  312.16     .06       0
  342.78     .12       0   429.3     .06       0   646.1    .045       0
     662     .06       0  700.89     .12       0  782.48     .06       0
     793     .12       0   863.4     .06       0  916.18     .12       0
  957.71     .06       0
Bank Sta=646.1,662
XS Rating Curve= 0 ,0
Exp/Cntr=0.3,0.1

Type RM Length L Ch R = 1 ,16044.2 ,502.9,511.4,519.4
XS GIS Cut Line= 3
     2424014.192      347670.245     2424780.251      347464.082
     2424897.439      347403.318
#Sta/Elev= 30
       0  468.04   12.35469.0401    39.9  471.44   73.21471.8011    83.7  471.25
  110.93467.4405   119.6  466.34   143.5  464.98   163.4   464.6  176.76465.0298
  219.96464.1916   259.1  463.73     295  464.28     307  463.78   326.9   464.4
   358.8  462.58   458.4  462.64   470.4     462   554.1  461.37   562.1  461.25
   566.1   461.3  619.62 461.933   681.7  462.55   721.6  463.96  748.86465.7448
   781.4  467.44  828.67468.4797   843.8  468.65   878.7  471.09   925.3  472.05
#Mann= 11 ,-1 , 0
       0     .06       0   12.35     .08       0   73.21     .06       0
  110.93     .12       0  176.76    .016       0  219.96     .06       0
   554.1    .045       0   566.1     .06       0  619.62     .12       0
  748.86     .06       0  828.67     .12       0
#XS Ineff= 2 , 0
          328.17  465.32
Permanent Ineff=
       F       F
Bank Sta=554.1,566.1
XS Rating Curve= 0 ,0
Exp/Cntr=0.3,0.1

Type RM Length L Ch R = 1 ,15532.8 ,369,366.2,379.9
XS GIS Cut Line= 3
     2424046.744      347930.662     2424743.359      347952.363
     2425045.008       347900.28
#Sta/Elev= 30
       0  471.33    51.8   471.2     161468.3405   199.1  466.79  240.07467.0475
   278.8  466.87   286.8  467.41  319.16464.4612  338.43463.4017   386.2  460.62
   390.3   460.5   398.3  460.55  481.28462.0122  486.23462.0549  564.01461.9773
   625.3  462.54     677   466.4   708.9  466.67   740.7  465.48   776.5  465.83
   808.3  470.08     844  471.08     856  470.76   891.8  474.54   907.6  474.95
   927.5   474.1   939.5  472.59   967.3  472.61   983.2  474.89  1003.1  476.03
#Mann= 10 ,-1 , 0
       0     .06       0     161    .016       0  240.07     .12       0
  319.16     .06       0  338.43     .12       0   386.2    .045       0
   398.3     .12       0  481.28     .08       0  486.23     .06       0
  564.01     .12       0
Bank Sta=386.2,398.3
XS Rating Curve= 0 ,0
Exp/Cntr=0.3,0.1

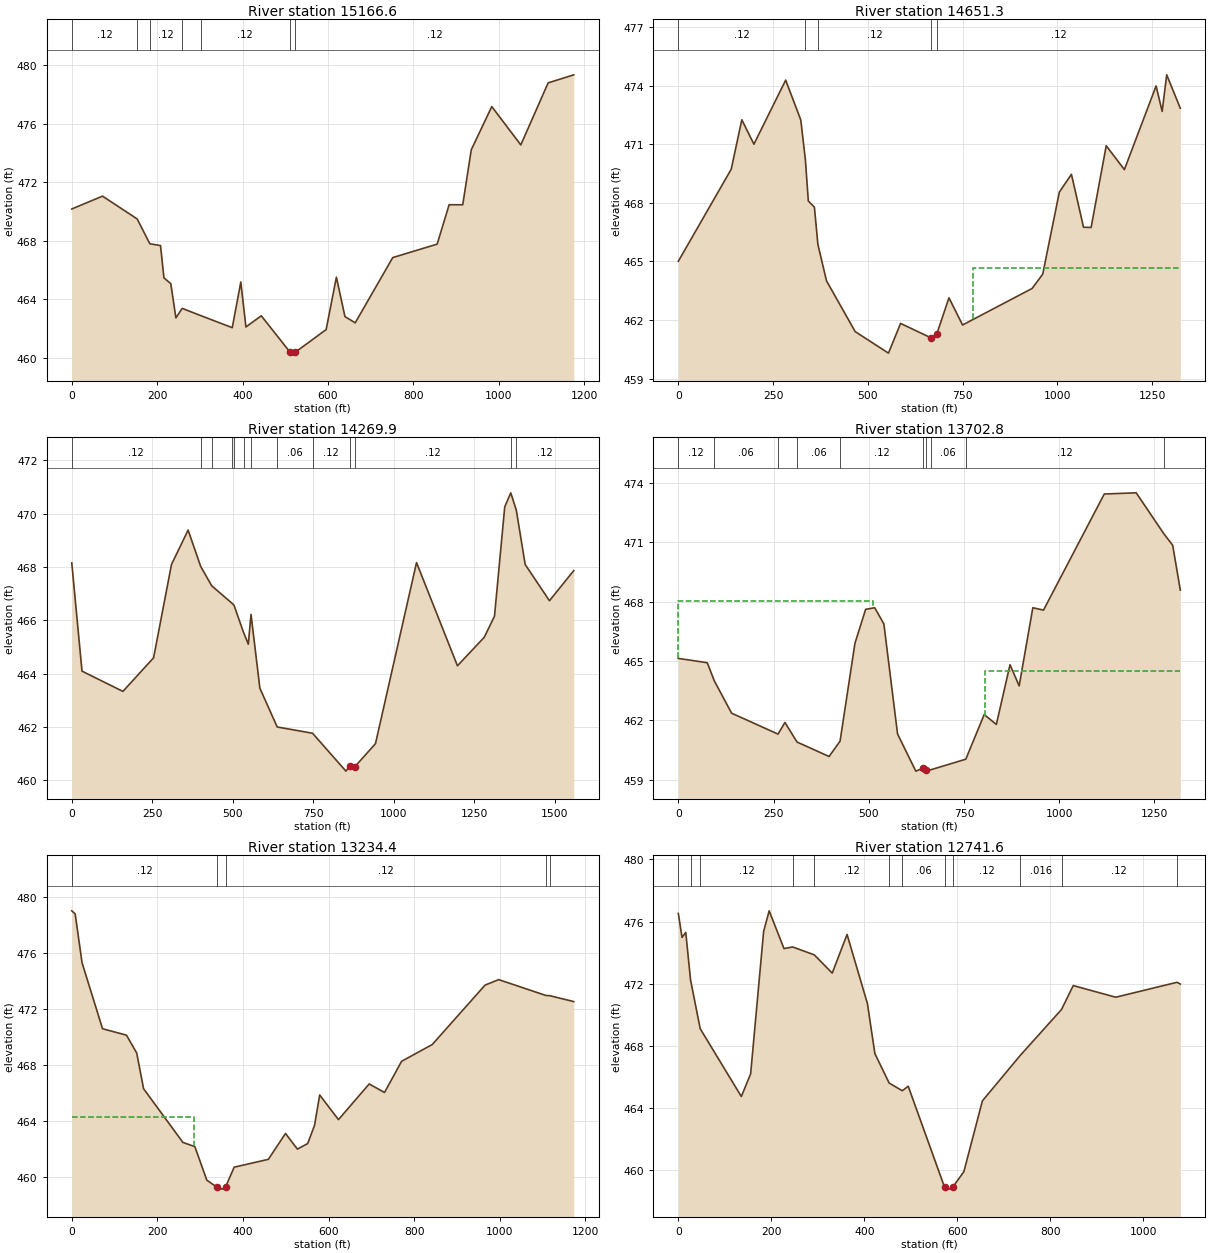
Type RM Length L Ch R = 1 ,15166.6 ,513.9,515.3,499
XS GIS Cut Line= 2
     2424061.067       348310.87     2425231.612      348201.304
#Sta/Elev= 30
       0  470.18      72  471.06  153.25469.4994  182.85467.8051   207.9  467.68
   215.9  465.47   231.9  465.08   243.9  462.74  258.77463.3894  302.18462.8933
   375.9  462.07   395.9  465.19   407.9  462.12   443.9  462.88  510.87  460.41
   515.8  460.33   523.8   460.4   595.8  461.94   619.8  465.52   639.8  462.83
   663.8   462.4   751.8  466.86   855.8  467.78   883.8  470.47   915.7  470.47
   935.7  474.23   983.7  477.18  1051.7  474.56  1115.7   478.8  1175.7  479.35
#Mann= 7 ,-1 , 0
       0     .12       0  153.25    .016       0  182.85     .12       0
  258.77    .016       0  302.18     .12       0  510.87    .045       0
   523.8     .12       0
Bank Sta=510.87,523.8
XS Rating Curve= 0 ,0
Exp/Cntr=0.3,0.1

Type RM Length L Ch R = 1 ,14651.3 ,380.5,381.5,381.9
XS GIS Cut Line= 2
     2424074.956      348678.925     2425398.307      348619.319
#Sta/Elev= 30
       0  465.01   139.6  469.72   167.6  472.25   199.5     471   283.3  474.28
   323.2  472.24  335.28470.2092   343.1  468.09   359.1  467.78  368.32465.8734
     391  464.01   466.8  461.41   554.6  460.31   586.5  461.83   667.5 461.085
   682.5 461.314   714.2  463.14   750.1  461.75   933.7  463.62   961.6  464.35
  1005.5  468.55  1037.4  469.46  1069.3  466.75  1089.3  466.74  1129.2  470.92
  1177.1   469.7  1260.8  473.98  1276.8  472.68  1288.8  474.55  1324.7  472.84
#Mann= 5 ,-1 , 0
       0     .12       0  335.28    .016       0  368.32     .12       0
   667.5    .045       0   682.5     .12       0
#XS Ineff= 2 , 0
                          778.74          464.68
Permanent Ineff=
       F       F
Bank Sta=667.5,682.5
XS Rating Curve= 0 ,0
Exp/Cntr=0.3,0.1

Type RM Length L Ch R = 1 ,14269.9 ,536.4,567.1,597.6
XS GIS Cut Line= 4
     2424035.894      348742.293     2424446.153      349007.581
     2424988.585      349022.241     2425398.307       349355.43
#Sta/Elev= 30
       0  468.16    31.8   464.1   158.9  463.34   254.2   464.6   309.8   468.1
   361.4  469.39  400.53468.0236   434.9467.2985   499.2466.6302  503.99466.5702
  533.53465.5526   548.4  465.11   556.8 466.228   584.3  463.46  638.17462.0052
  747.82461.7714   851.6  460.35   863.6  460.54   879.6  460.52   943.4  461.38
  1070.9  468.17    1198   464.3  1281.3  465.37  1313.1  466.16  1344.9  470.26
 1363.63470.7866 1380.84470.1388  1408.4   468.1  1483.8  466.74  1559.3  467.87
#Mann= 13 ,-1 , 0
       0     .12       0  400.53     .06       0   434.9    .016       0
   499.2     .06       0  503.99     .12       0  533.53    .016       0
   556.8     .12       0  638.17     .06       0  747.82     .12       0
   863.6    .045       0   879.6     .12       0 1363.63     .06       0
 1380.84     .12       0
Bank Sta=863.6,879.6
XS Rating Curve= 0 ,0
Exp/Cntr=0.3,0.1

Type RM Length L Ch R = 1 ,13702.8 ,491.1,468.4,445.5
XS GIS Cut Line= 3
      2423970.79      348900.714     2424392.867      349168.318
     2424558.463      349969.579
#Sta/Elev= 30
       0  465.14      76  464.92   94.33 464.011   139.9  462.37  261.88461.3105
   279.9   461.9  311.67460.9113   395.8  460.18  424.69460.9557   463.8  465.91
   491.8  467.62   515.7   467.7   539.7  466.88   575.6  461.32   623.5  459.44
   643.4  459.59   651.4   459.5  662.71459.5079  754.78460.0426   803.1   462.3
     835   461.8   870.9  464.82   894.9  463.75   930.8   467.7   958.8  467.58
  1118.4  473.45  1202.2  473.51  1274.7 471.442    1298  470.86    1318  468.59
#Mann= 10 ,-1 , 0
       0     .12       0   94.33     .06       0  261.88    .016       0
  311.67     .06       0  424.69     .12       0   643.4    .045       0
   651.4     .12       0  662.71     .06       0  754.78     .12       0
  1274.7     .06       0
#XS Ineff= 2 , 0
          511.46  468.05  806.19          464.51
Permanent Ineff=
       F       F
Bank Sta=643.4,651.4
XS Rating Curve= 0 ,0
Exp/Cntr=0.3,0.1

Type RM Length L Ch R = 1 ,13234.4 ,500,492.8,484.9
XS GIS Cut Line= 3
     2423771.137      349241.425     2424376.606      349458.439
     2424523.741      349967.409
#Sta/Elev= 30
       0  479.04       8  478.82      24  475.33    71.9  470.61   127.8  470.15
   151.8  468.87   167.8  466.32   259.7  462.48   287.6  462.18   315.6  459.78
   339.6  459.27   351.6  459.14   359.5   459.3   379.5  460.71   459.4  461.27
   499.4  463.12   527.3     462   551.3   462.4   567.3   463.7   579.3  465.87
   623.2  464.11     695  466.66   730.8  466.05   770.7  468.28   842.4  469.48
   965.8  473.73   997.7  474.12 1107.95472.9869 1116.81472.9729    1173  472.55
#Mann= 5 ,-1 , 0
       0     .12       0   339.6    .045       0   359.5     .12       0
 1107.95     .06       0 1116.81     .12       0
#XS Ineff= 2 , 0
          286.07  464.33
Permanent Ineff=
       F       F
Bank Sta=339.6,359.5
XS Rating Curve= 0 ,0
Exp/Cntr=0.3,0.1

Type RM Length L Ch R = 1 ,12741.6 ,430.9,462,492.7
XS GIS Cut Line= 3
     2423491.667      349784.203     2424324.522      349807.832
     2424493.359       349986.94
#Sta/Elev= 30
       0  476.52       8  474.98      16   475.3   26.31472.2411   47.05469.1038
   135.5  464.74   155.5   466.2   183.4  475.36   195.3  476.69   227.2  474.26
  245.81474.3648  292.32473.8569   330.9  472.68   362.8  475.17   406.6  470.72
   422.6   467.5  453.35 465.606  481.44465.1128   494.3   465.4  572.42458.9046
     582  458.78     590  458.91   613.9   459.9   653.8  464.46   734.8 467.373
  823.86470.3395   849.1  471.88   940.4  471.13 1072.19472.0901  1079.3  471.98
#Mann= 12 ,-1 , 0
       0     .12       0   26.31     .06       0   47.05     .12       0
  245.81     .06       0  292.32     .12       0  453.35     .08       0
  481.44     .06       0  572.42    .045       0     590     .12       0
   734.8    .016       0  823.86     .12       0 1072.19     .06       0
Bank Sta=572.42,590
XS Rating Curve= 0 ,0
Exp/Cntr=0.3,0.1

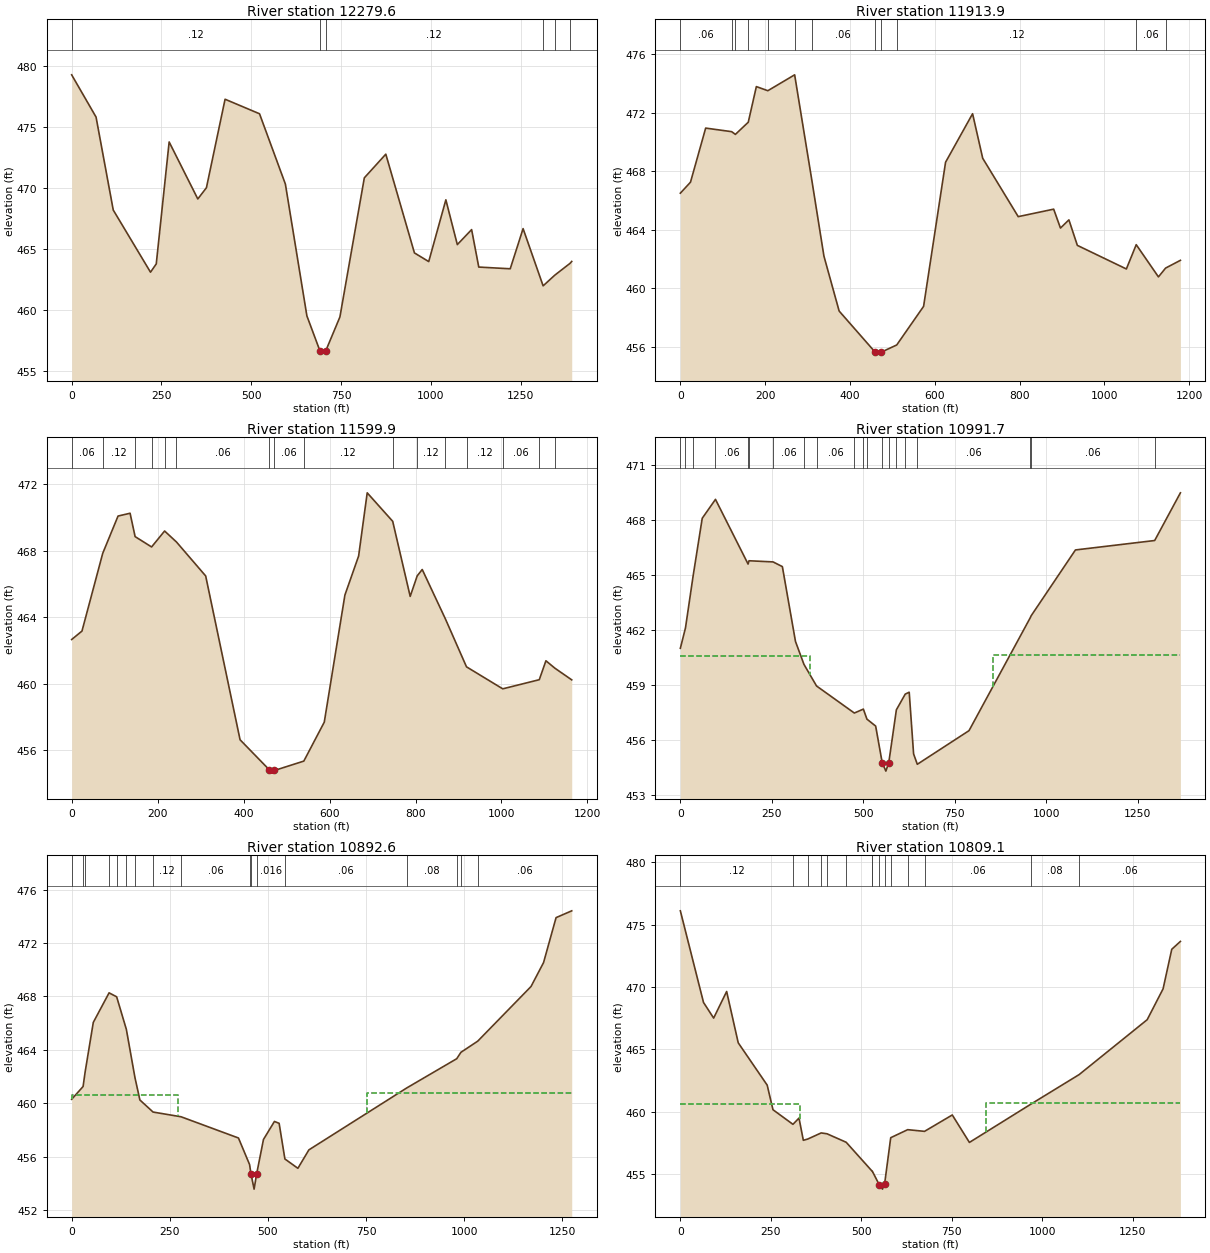
Type RM Length L Ch R = 1 ,12279.6 ,404.8,365.7,325.8
XS GIS Cut Line= 4
     2423436.111      349867.537     2423863.195      349867.537
     2423943.056      350287.676     2424467.361      350405.731
#Sta/Elev= 30
       0  479.27    67.9  475.81   115.8  468.19   219.5   463.1   235.5  463.78
   271.4  473.77   351.2   469.1   375.2  470.02   427.1  477.27     523  476.08
     595  470.32   654.9  459.52   690.9  456.68   698.9  456.47   706.9  456.62
   746.8  459.43   814.8  470.83   874.6  472.77   954.3  464.68   994.1  463.97
  1041.8  469.03  1073.7  465.36  1113.5  466.59  1133.4  463.52    1221  463.38
  1256.8  466.67 1312.56461.9807 1345.07462.8566 1387.37463.8217  1392.2  463.98
#Mann= 6 ,-1 , 0
       0     .12       0   690.9    .045       0   706.9     .12       0
 1312.56    .016       0 1345.07     .12       0 1387.37     .06       0
Bank Sta=690.9,706.9
XS Rating Curve= 0 ,0
Exp/Cntr=0.3,0.1

Type RM Length L Ch R = 1 ,11913.9 ,313.6,314,314.2
XS GIS Cut Line= 3
     2423297.222      350471.703     2423894.445      350315.453
     2424439.584       350450.87
#Sta/Elev= 30
       0   466.5    23.9  467.25    59.7  470.94  120.98470.6956  129.75470.5094
  160.13  471.34   179.2  473.77  206.26473.4895  269.46474.5731  310.39467.3115
   338.5  462.21   374.4  458.46     458   455.7     470  455.59     474  455.66
  510.14 456.146   573.5  458.78   625.3  468.61     689  471.92   712.9  468.88
   796.6   464.9   880.2  465.41   896.2  464.12   916.1  464.68     936  462.94
  1051.6  461.33 1074.83462.9876  1127.2  460.79  1144.1461.3915    1179  461.92
#Mann= 12 ,-1 , 0
       0     .06       0  120.98     .12       0  129.75     .06       0
  160.13    .016       0  206.26     .12       0  269.46     .08       0
  310.39     .06       0     458    .045       0     474     .06       0
  510.14     .12       0 1074.83     .06       0  1144.1    .016       0
Bank Sta=458,474
XS Rating Curve= 0 ,0
Exp/Cntr=0.3,0.1

Type RM Length L Ch R = 1 ,11599.9 ,578.5,608.1,637.4
XS GIS Cut Line= 2
     2423364.887       350768.19     2424495.139      350492.537
#Sta/Elev= 30
       0  462.65      24  463.16   72.27467.8456   107.9  470.09   135.9  470.26
  147.62468.8513  185.95468.2282  216.21469.1893  243.75468.5292   311.8  466.48
   391.8  456.61   459.8   454.8   467.8  454.72   471.8  454.76  540.11455.3241
   587.7  457.67   635.7  465.33   667.6  467.68   687.6  471.49  746.88469.7742
   787.6  465.25   803.9466.4855   815.6  466.87  869.71463.8806  918.59 461.005
 1002.93459.6786 1087.92 460.229  1103.4  461.37 1123.96460.9282  1163.4  460.22
#Mann= 16 ,-1 , 0
       0     .06       0   72.27     .12       0  147.62     .06       0
  185.95     .08       0  216.21    .016       0  243.75     .06       0
   459.8    .045       0   471.8     .06       0  540.11     .12       0
  746.88     .06       0   803.9     .12       0  869.71     .06       0
  918.59     .12       0 1002.93     .06       0 1087.92    .016       0
 1123.96     .12       0
Bank Sta=459.8,471.8
XS Rating Curve= 0 ,0
Exp/Cntr=0.3,0.1

Type RM Length L Ch R = 1 ,10991.7 ,99.1,99.1,99.1
XS GIS Cut Line= 3
     2423395.266      350814.278     2423609.676      350752.646
     2424215.578      351723.132
#Sta/Elev= 30
       0  461.01   14.01462.1228   34.91464.9634    59.8  468.11   96.04469.1421
  185.19465.6093  187.74465.7897  253.52465.7267   278.9  465.47   314.8  461.38
  337.92460.1312  372.36458.9508  475.68457.4726  500.39457.6875  510.11457.1399
     534  456.76  551.84454.7644   561.9   454.3   569.9  454.77  590.62457.6485
   614.9458.5075   625.7  458.61   637.7  455.24  647.87454.6743   789.2  456.51
  957.07462.6923  958.84462.7764  1080.2  466.38 1296.85466.8954  1367.2   469.5
#Mann= 20 ,-1 , 0
       0     .06       0   14.01     .12       0   34.91     .08       0
   96.04     .06       0  185.19     .08       0  187.74    .016       0
  253.52     .06       0  337.92     .08       0  372.36     .06       0
  475.68     .12       0  500.39     .08       0  510.11     .06       0
  551.84    .045       0   569.9     .06       0  590.62    .016       0
   614.9     .12       0  647.87     .06       0  957.07     .12       0
  958.84     .06       0 1296.85     .12       0
#XS Ineff= 2 , 0
          355.42  460.59  853.87          460.62
Permanent Ineff=
       F       F
Bank Sta=551.84,569.9
XS Rating Curve= 0 ,0
Exp/Cntr=0.3,0.1

Type RM Length L Ch R = 1 ,10892.6 ,81,83.5,86
XS GIS Cut Line= 3
     2423396.134      350829.035     2423521.134      350793.444
     2424127.037       351763.93
#Sta/Elev= 30
       0  460.29   29.11461.2481   34.24462.3239    55.1  466.05   95.33468.2657
  114.65467.9676  139.36465.5266  161.26461.9148   173.8  460.24  207.41459.3345
  278.76458.9805     425  457.39  453.31455.4006   456.8  454.72   464.8  453.56
   471.5 454.726   488.7  457.28   516.6  458.63   528.6  458.49   543.3455.8185
   576.4  455.12   604.4   456.5  853.25461.1319  981.12463.3305  991.84463.8115
 1034.56 464.644  1170.4  468.74  1202.3  470.53  1234.2   473.9  1274.1  474.41
#Mann= 17 ,-1 , 0
       0     .06       0   29.11     .12       0   34.24     .08       0
   95.33     .12       0  114.65     .06       0  139.36     .12       0
  161.26     .06       0  207.41     .12       0  278.76     .06       0
  453.31    .016       0   456.8    .045       0   471.5    .016       0
   543.3     .06       0  853.25     .08       0  981.12     .06       0
  991.84     .08       0 1034.56     .06       0
#XS Ineff= 2 , 0
          270.18  460.64  752.73          460.73
Permanent Ineff=
       F       F
Bank Sta=456.8,471.5
XS Rating Curve= 0 ,0
Exp/Cntr=0.3,0.1

Type RM Length L Ch R = 1 ,10809.1 ,179.1,168,154
XS GIS Cut Line= 5
     2423180.856      351069.486     2423547.176      350954.903
     2423660.891      351191.014     2423778.946      351251.778
     2424102.731      351760.458
#Sta/Elev= 30
       0   476.1      64  468.76      92  467.51   127.9  469.64   159.9  465.53
   239.9  462.14   255.9  460.17   311.1     459   327.8   459.5   339.8  457.72
  352.09457.8223  389.07458.3105  405.21458.2422  458.12457.5644  530.28455.2335
  530.57 455.238   549.5  454.16   558.5  453.81   564.5  454.26  581.21457.9291
  628.13 458.572   674.6458.4374   751.3  459.75   798.6  457.55  969.93460.6425
 1101.63  462.98  1289.8  467.38  1333.7  469.85  1357.7  473.02  1381.6  473.65
#Mann= 15 ,-1 , 0
       0     .12       0   311.1     .06       0  352.09     .12       0
  389.07     .06       0  405.21     .08       0  458.12     .06       0
  530.28     .12       0  530.57     .06       0   549.5    .045       0
   564.5     .06       0  581.21    .016       0  628.13     .08       0
   674.6     .06       0  969.93     .08       0 1101.63     .06       0
#XS Ineff= 2 , 0
          329.41  460.64   845.2          460.69
Permanent Ineff=
       F       F
Bank Sta=549.5,564.5
XS Rating Curve= 0 ,0
Exp/Cntr=0.3,0.1