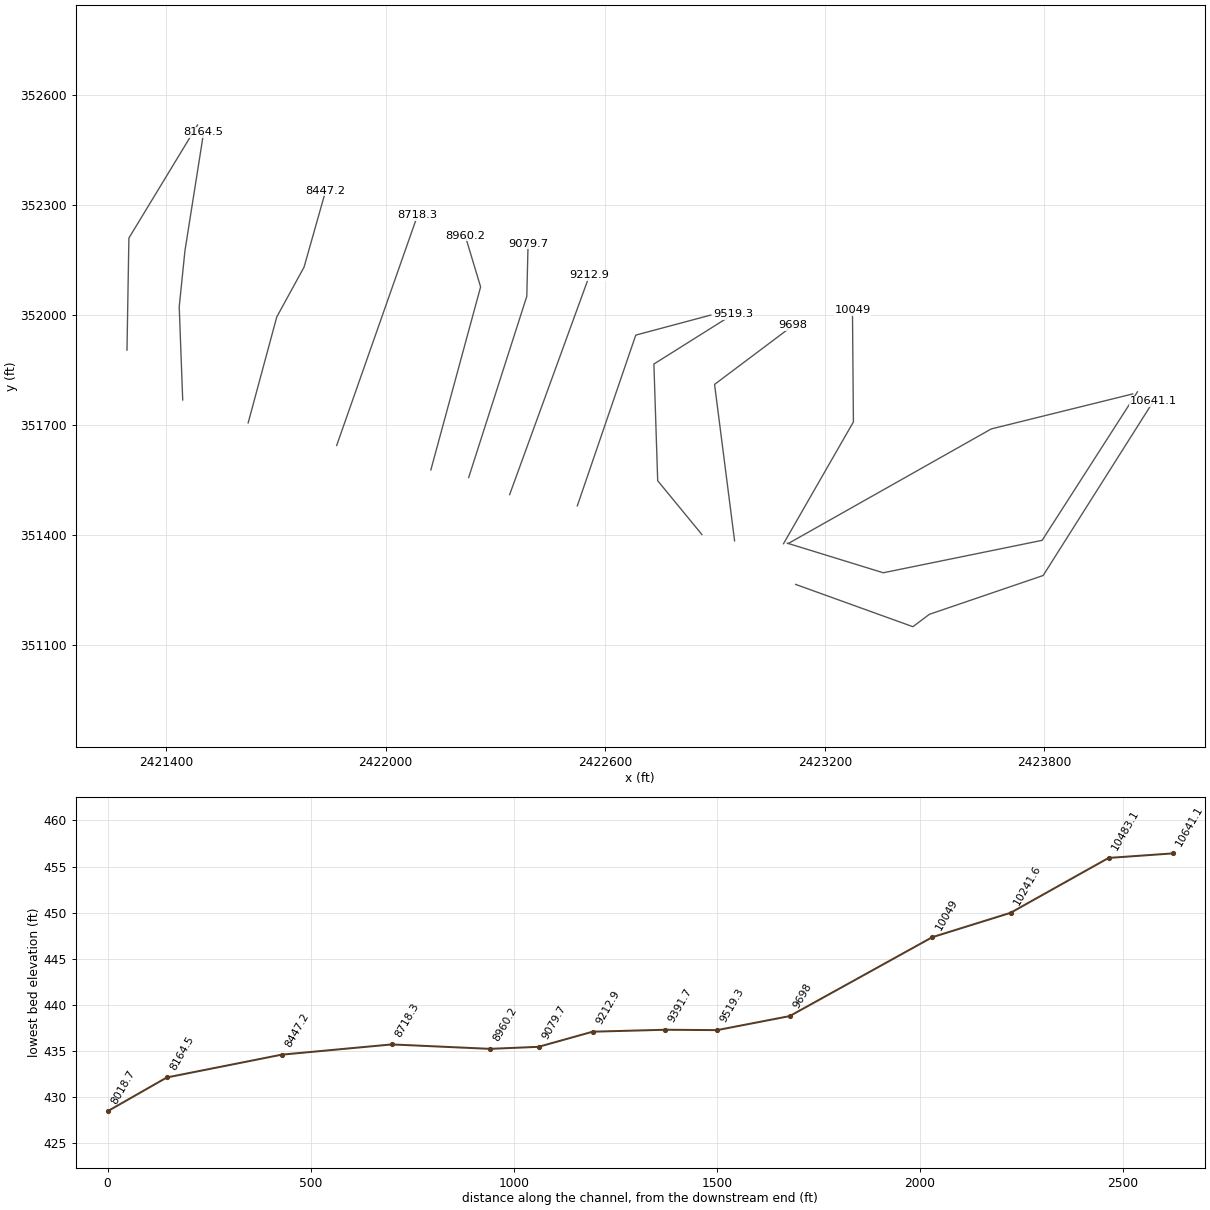
HEC-RAS study OPQNTRIB2.prj: OPQNTRIB2

--- OPQNTRIB2.g01 (geometry) --- (continued)

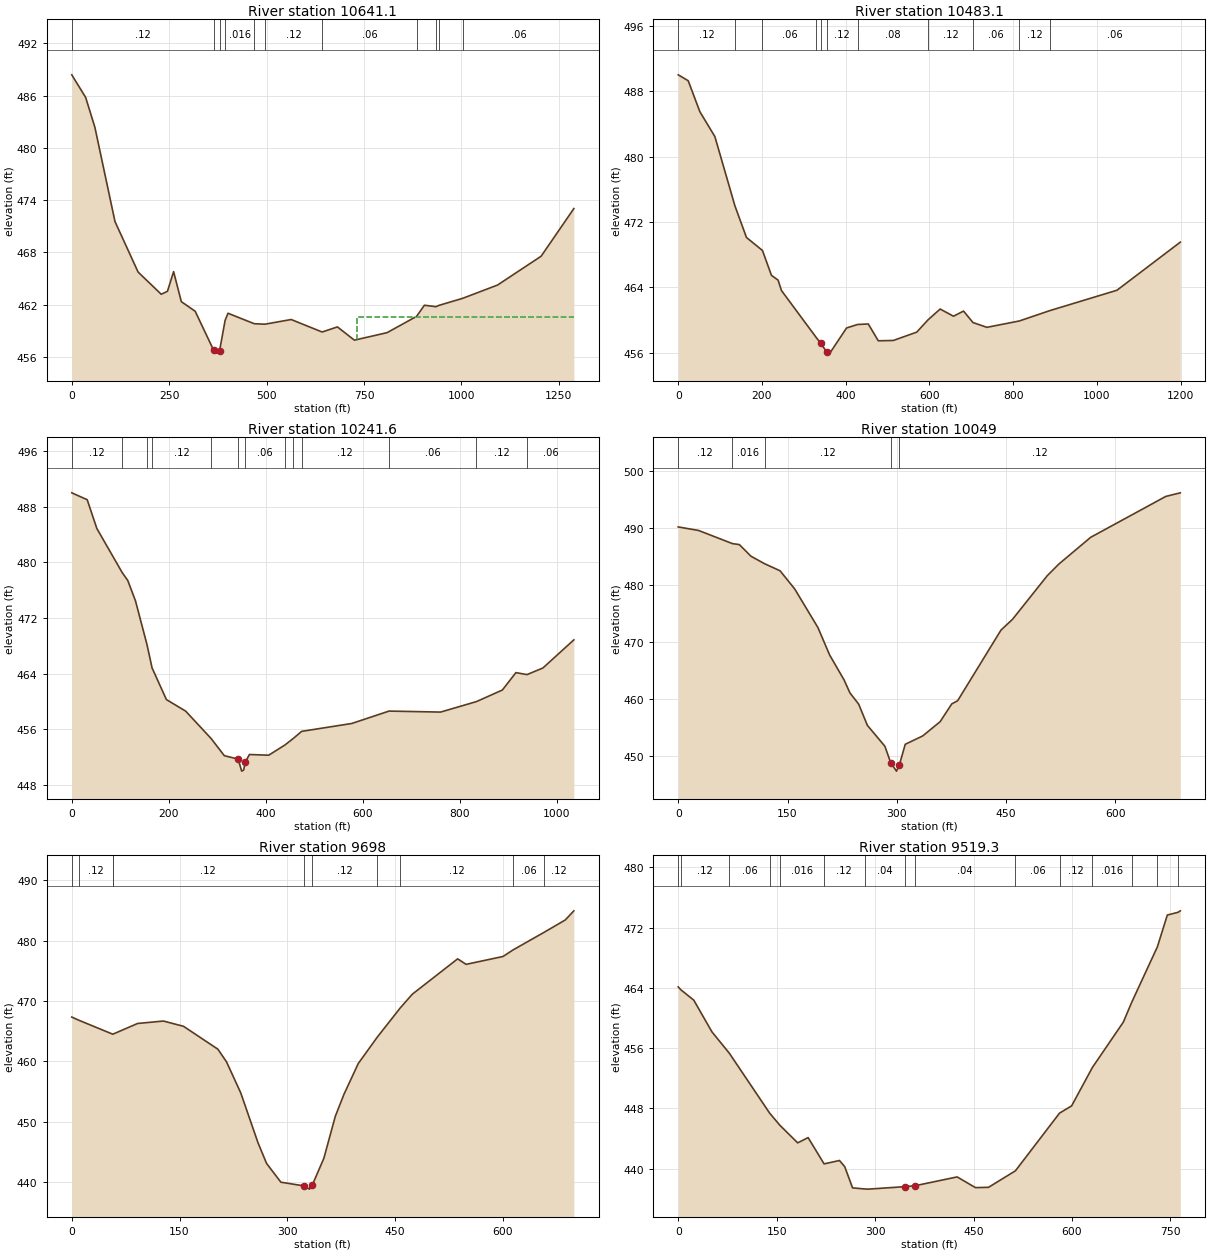
Type RM Length L Ch R = 1 ,10641.1 ,169.1,158,149.8
XS GIS Cut Line= 5
     2423120.266      351264.799     2423440.578      351149.347
     2423485.717      351183.201     2423796.481      351289.104
     2424097.696      351764.799
#Sta/Elev= 30
       0  488.39    35.6   485.8    59.4  482.35   110.9  471.54   170.2  465.74
   229.6  463.19   245.5  463.53   261.3  465.79   281.1  462.34   316.7  461.24
   364.2  456.75   374.3  456.43   379.2  456.68  393.51460.1978   400.9  461.01
  468.16459.8092  495.68459.7515     563  460.29  642.37458.8556   681.7  459.44
   725.2  457.92   809.1  458.78  884.75460.6494   904.9  461.93  934.52461.7643
  941.41461.9029 1003.66462.7327  1092.6  464.25  1204.4  467.56  1288.3  473.03
#Mann= 11 ,-1 , 0
       0     .12       0   364.2    .045       0   379.2     .12       0
  393.51    .016       0  468.16     .08       0  495.68     .12       0
  642.37     .06       0  884.75     .08       0  934.52     .12       0
  941.41     .08       0 1003.66     .06       0
#XS Ineff= 2 , 0
                          731.06          460.56
Permanent Ineff=
       F       F
Bank Sta=364.2,379.2
XS Rating Curve= 0 ,0
Exp/Cntr=0.3,0.1

Type RM Length L Ch R = 1 ,10483.1 ,234.5,241.5,248.6
XS GIS Cut Line= 4
     2423097.523      351377.299     2423359.676      351296.569
     2423793.703      351385.111      2424054.12      351790.493
#Sta/Elev= 30
       0  490.02    23.8   489.3    51.7   485.5    87.5  482.46  135.37473.9769
     163   470.1  201.14 468.512   222.6  465.47   238.5  464.88   246.5  463.61
  329.88457.8312   339.9  457.17   354.9  456.08   362.1  455.94     402  459.02
  428.37459.4478   453.9  459.51   477.8  457.45   513.7  457.49   569.6  458.51
  596.32460.0032   625.5  461.34   657.4  460.46   681.4  461.09  703.92459.6841
   737.2   459.1  814.55459.8756  886.88461.1357  1047.8  463.64  1199.1  469.53
#Mann= 11 ,-1 , 0
       0     .12       0  135.37    .016       0  201.14     .06       0
  329.88     .12       0   339.9    .045       0   354.9     .12       0
  428.37     .08       0  596.32     .12       0  703.92     .06       0
  814.55     .12       0  886.88     .06       0
Bank Sta=339.9,354.9
XS Rating Curve= 0 ,0
Exp/Cntr=0.3,0.1

Type RM Length L Ch R = 1 ,10241.6 ,180.2,192.6,204.6
XS GIS Cut Line= 3
     2423100.163      351376.485     2423654.814      351689.278
     2424041.099      351784.764
#Sta/Elev= 30
       0     490    31.8  489.01    51.7  484.87  104.07478.5187   115.4   477.4
   131.3  474.47  155.05468.1755  165.48 464.833     195  460.28   234.8  458.61
   287.4454.6595   314.4  452.21   342.8  451.72   350.2  449.99   354.2  450.14
   357.8  451.31   366.1  452.38   405.9  452.28   439.2 453.742  456.87454.7068
  473.76 455.706   577.1  456.84  653.81458.6211   760.1  458.48  834.02459.9871
   887.4  461.65   915.3  464.15  938.25463.8685     971  464.82  1034.7  468.86
#Mann= 13 ,-1 , 0
       0     .12       0  104.07    .016       0  155.05     .06       0
  165.48     .12       0   287.4     .06       0   342.8    .045       0
   357.8     .06       0   439.2     .12       0  456.87     .06       0
  473.76     .12       0  653.81     .06       0  834.02     .12       0
  938.25     .06       0
Bank Sta=342.8,357.8
XS Rating Curve= 0 ,0
Exp/Cntr=0.3,0.1

Type RM Length L Ch R = 1 ,10049   ,336.2,351.1,365.8
XS GIS Cut Line= 3
     2423087.106       351375.91     2423278.078      351708.375
     2423275.474       352013.93
#Sta/Elev= 30
       0  490.22      28   489.6   74.35487.2952    83.9  487.12    99.8  485.08
  118.41 483.769   139.8  482.52   159.8  479.34   191.7  472.56   207.7  467.76
   227.6  463.36   235.6  461.09   247.6  459.12   259.6  455.38   283.6  451.72
   291.6  448.82   299.5  447.35   303.5  448.46   311.5  452.06   335.5  453.53
   359.4  456.03   375.4  459.16   383.4   459.7   442.9  472.11   458.8  474.01
   506.4  481.66   522.3   483.7     566   488.4   669.1  495.58     689  496.21
#Mann= 5 ,-1 , 0
       0     .12       0   74.35    .016       0  118.41     .12       0
   291.6    .045       0   303.5     .12       0
Bank Sta=291.6,303.5
XS Rating Curve= 0 ,0
Exp/Cntr=0.3,0.1

Type RM Length L Ch R = 1 ,9698    ,180.6,178.7,176.8
XS GIS Cut Line= 3
     2422953.426      351383.722     2422898.738      351810.805
     2423113.195      351971.703
#Sta/Elev= 30
       0  467.32    9.61466.8076   57.02464.4814   57.22464.4849    91.7  466.26
   127.6  466.66   155.5  465.79   203.3     462   215.3  459.91   235.2  454.74
   259.1  446.51   271.1  443.06     291  439.95   322.9  439.34   330.9   438.8
   334.9  439.52   350.8  443.91   366.8  450.89   378.7  454.49   398.7  459.62
  425.26464.0092  457.05468.8245   473.9  471.11     537  476.97   548.8  476.06
   600.1  477.36  614.16478.4547  656.79481.3317   686.8  483.42   698.7  484.93
#Mann= 10 ,-1 , 0
       0     .08       0    9.61     .12       0   57.02     .06       0
   57.22     .12       0   322.9    .045       0   334.9     .12       0
  425.26     .06       0  457.05     .12       0  614.16     .06       0
  656.79     .12       0
Bank Sta=322.9,334.9
XS Rating Curve= 0 ,0
Exp/Cntr=0.3,0.1

Type RM Length L Ch R = 1 ,9519.3  ,136.1,127.6,119.1
XS GIS Cut Line= 4
     2422864.016      351401.083     2422743.356      351547.785
     2422732.939      351866.361     2422949.953      352002.646
#Sta/Elev= 30
       0  464.12    4.05463.7364    23.7  462.36    51.4  458.15   77.74 455.333
  139.26447.3731  154.56445.7859     182  443.42   197.9  444.12  222.22440.6326
   245.7  441.08   253.7  440.26   265.6  437.45  283.96437.2982   289.6  437.28
   345.8  437.61   360.8  437.73     425   438.9   452.9  437.48   472.8  437.52
  513.79 439.713  580.98447.3677   599.4  448.33  631.07453.4326   678.2  459.45
   690.9462.0653  730.07469.4428   745.2  473.66  761.34474.0187     765  474.22
#Mann= 15 ,-1 , 0
       0    .016       0    4.05     .12       0   77.74     .06       0
  139.26     .12       0  154.56    .016       0  222.22     .12       0
  283.96     .04       0   345.8    .045       0   360.8     .04       0
  513.79     .06       0  580.98     .12       0  631.07    .016       0
   690.9     .12       0  730.07    .016       0  761.34     .06       0
Bank Sta=345.8,360.8
XS Rating Curve= 0 ,0
Exp/Cntr=0.3,0.1

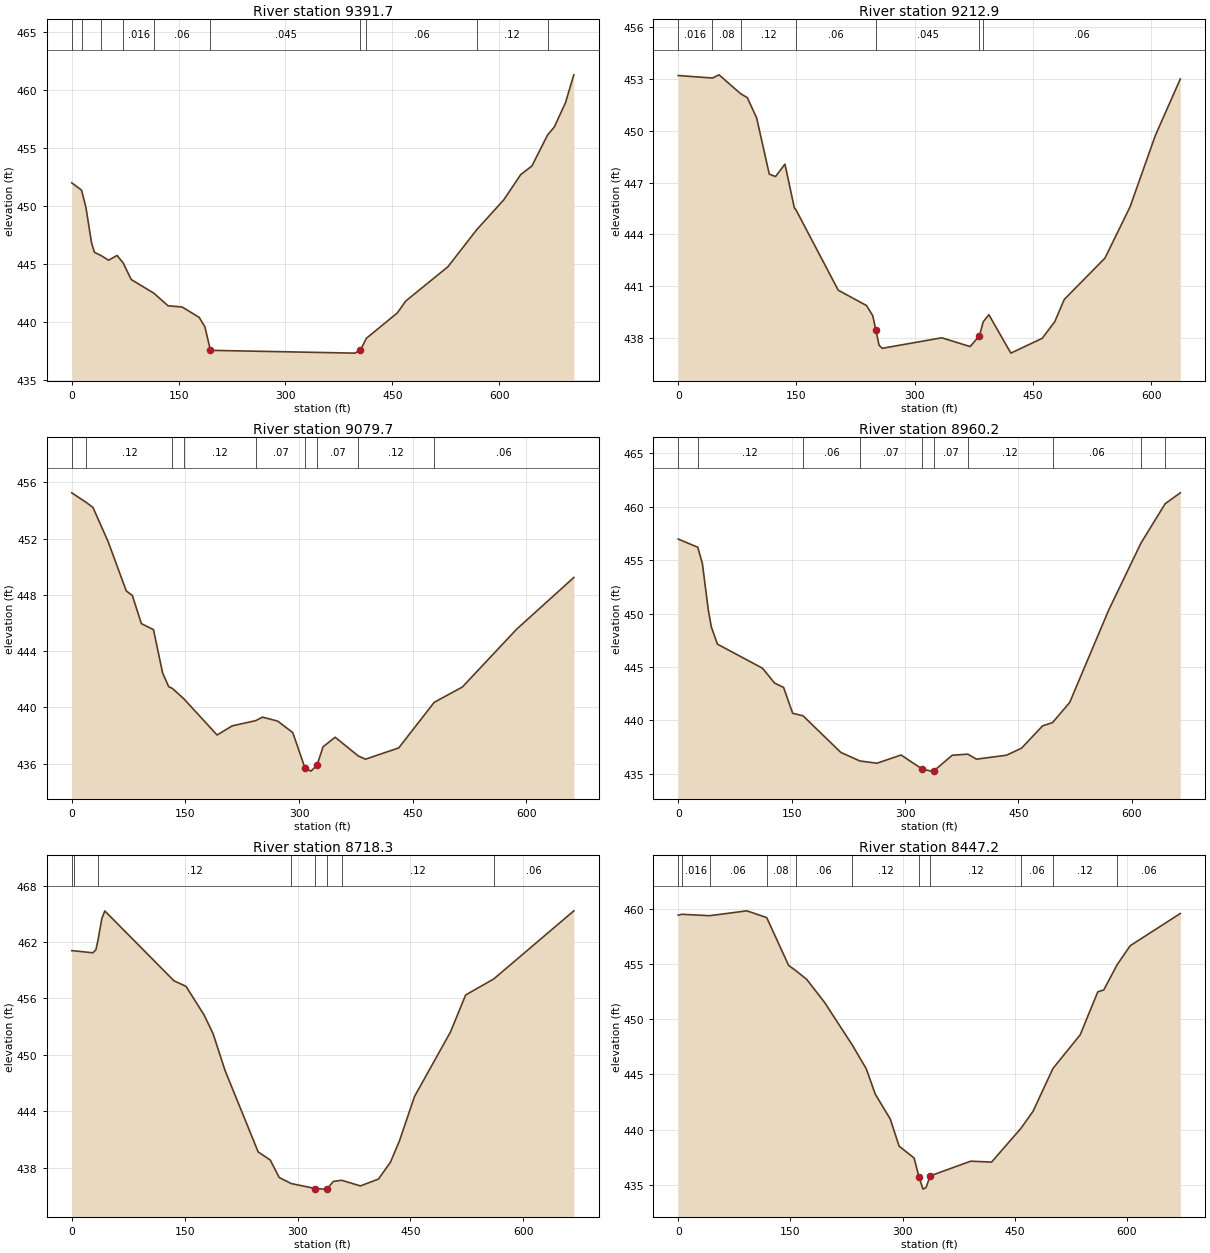
Type RM Length L Ch R = 1 ,9391.7  ,179.2,178.8,178.3
XS GIS Cut Line= 3
     2422523.738      351479.208      2422683.46      351945.354
     2422888.321      352000.042
#Sta/Elev= 30
       0  451.98   13.76451.3496    19.9  449.86    27.8   446.8    31.8     446
   41.22445.7178    51.7  445.32    63.6  445.73   72.24445.0749    83.4  443.66
  115.14442.4837   135.1   441.4     155  441.29   178.8   440.4   186.8   439.6
   194.7  437.56   397.4  437.32   405.3  437.58  413.51438.5951     457  440.78
   468.9  441.81   528.1  444.76  568.52447.9519   606.6  450.53   630.2  452.69
   645.9  453.43  668.01 456.111   677.3  456.78     693  458.87   704.8  461.28
#Mann= 10 ,-1 , 0
       0    .016       0   13.76     .12       0   41.22     .06       0
   72.24    .016       0  115.14     .06       0   194.7    .045       0
   405.3     .04       0  413.51     .06       0  568.52     .12       0
  668.01    .016       0
Bank Sta=194.7,405.3
XS Rating Curve= 0 ,0
Exp/Cntr=0.3,0.1

Type RM Length L Ch R = 1 ,9212.9  ,132.4,133.3,134.2
XS GIS Cut Line= 3
      2422338.83       351509.94     2422447.899      351809.182
     2422556.969      352108.425
#Sta/Elev= 30
       0  453.21   43.45453.0646    51.8  453.25   79.27452.1507    87.6  451.93
    99.5  450.75   115.5  447.49   123.4  447.35   135.4  448.07   147.3  445.54
  149.57445.4038     203  440.76   238.9  439.87   246.8  439.28   250.8  438.43
   254.8  437.57   258.8  437.39   334.4     438   370.3  437.49   382.2  438.12
  386.94438.9254   394.1  439.34     422  437.11   461.8  437.97   477.8  438.94
   489.7  440.22   541.4  442.62   573.3   445.6   605.2  449.72     637  453.01
#Mann= 7 ,-1 , 0
       0    .016       0   43.45     .08       0   79.27     .12       0
  149.57     .06       0   250.8    .045       0   382.2     .04       0
  386.94     .06       0
Bank Sta=250.8,382.2
XS Rating Curve= 0 ,0
Exp/Cntr=0.3,0.1

Type RM Length L Ch R = 1 ,9079.7  ,118.4,119.4,120.4
XS GIS Cut Line= 3
     2422226.863      351556.465     2422385.717      352051.257
     2422389.189      352194.486
#Sta/Elev= 30
       0  455.26   19.31454.5717      28  454.22      48  451.79      72  448.28
      80  447.96    91.9  445.96   107.9  445.53   119.9  442.46   127.9  441.48
  132.91441.3497  147.76440.6252   191.9  438.04   211.9  438.69  242.92439.0602
   251.8  439.31   271.8  439.03   291.8  438.21   307.8  435.71   315.8  435.47
   323.8  435.89   331.8   437.2   347.8  437.88  378.39436.5429   387.8  436.32
   431.7  437.12  478.53440.3625   515.7  441.45   587.3  445.56   662.9  449.24
#Mann= 9 ,-1 , 0
       0    .016       0   19.31     .12       0  132.91     .06       0
  147.76     .12       0  242.92     .07       0   307.8    .045       0
   323.8     .07       0  378.39     .12       0  478.53     .06       0
Bank Sta=307.8,323.8
XS Rating Curve= 0 ,0
Exp/Cntr=0.3,0.1

Type RM Length L Ch R = 1 ,8960.2  ,243.6,242,240.3
XS GIS Cut Line= 3
     2422123.564      351577.299     2422259.519      352076.978
     2422217.314      352217.055
#Sta/Elev= 30
       0  456.97   25.77456.2103    31.9   454.7    39.8  450.32    43.8  448.75
    51.8  447.14   111.5  444.88   127.5  443.49   139.4  443.08   151.4  440.66
  164.97440.4358   215.1     437  240.34   436.2   262.9  435.99   294.8  436.76
   322.7  435.44   334.6  435.25   338.6   435.3   362.5  436.74  383.12436.8378
   394.4  436.37   434.2  436.74   454.1   437.4     482  439.49  495.14439.7944
   517.8  441.68   569.2   450.3  611.98456.5858  644.05460.2811   664.1   461.3
#Mann= 10 ,-1 , 0
       0    .016       0   25.77     .12       0  164.97     .06       0
  240.34     .07       0   322.7    .045       0   338.6     .07       0
  383.12     .12       0  495.14     .06       0  611.98     .12       0
  644.05     .06       0
Bank Sta=322.7,338.6
XS Rating Curve= 0 ,0
Exp/Cntr=0.3,0.1

Type RM Length L Ch R = 1 ,8718.3  ,275.1,271.1,267.3
XS GIS Cut Line= 2
     2421866.233      351644.012     2422087.587      352273.353
#Sta/Elev= 30
       0  461.08    3.57461.0621      28  460.86      32  461.17   34.67462.1179
      40  464.51    43.9  465.31   135.8  457.88   151.8  457.29   175.8  454.25
   187.8  452.25   203.7  448.34   247.7  439.68   263.7  438.83   275.6  436.97
  291.52 436.324   323.8  435.79   335.6  435.73   338.8  435.73   347.6  436.55
  358.61436.6711   383.5  436.07   407.5   436.8   423.4  438.59   435.4  440.86
   455.4  445.58   503.4  452.47   523.3  456.37  560.81458.0844   667.1  465.32
#Mann= 8 ,-1 , 0
       0     .12       0    3.57    .016       0   34.67     .12       0
  291.52     .07       0   323.8    .045       0   338.8     .07       0
  358.61     .12       0  560.81     .06       0
Bank Sta=323.8,338.8
XS Rating Curve= 0 ,0
Exp/Cntr=0.3,0.1

Type RM Length L Ch R = 1 ,8447.2  ,273.3,282.7,291.6
XS GIS Cut Line= 4
     2421624.433      351705.771     2421702.558      351994.833
      2421777.21      352131.118     2421836.238      352339.451
#Sta/Elev= 30
       0  459.43    4.82 459.508   41.81459.3782    91.8  459.82  118.32459.2073
   147.7  454.87  157.01454.4176   171.7  453.62   195.6  451.54  232.42447.7057
   251.5  445.51   263.5  443.22   283.5  440.97   295.4  438.51   315.4  437.44
     322   435.7   327.3  434.62   331.3  434.76     337  435.82   391.1  437.15
     419  437.07  458.18440.1173   474.5  441.67  501.04445.5425   537.5  448.59
   561.1  452.49     569  452.65  587.03454.9544   604.4  456.66   671.4  459.58
#Mann= 11 ,-1 , 0
       0     .08       0    4.82    .016       0   41.81     .06       0
  118.32     .08       0  157.01     .06       0  232.42     .12       0
     322    .045       0     337     .12       0  458.18     .06       0
  501.04     .12       0  587.03     .06       0
Bank Sta=322,337
XS Rating Curve= 0 ,0
Exp/Cntr=0.3,0.1

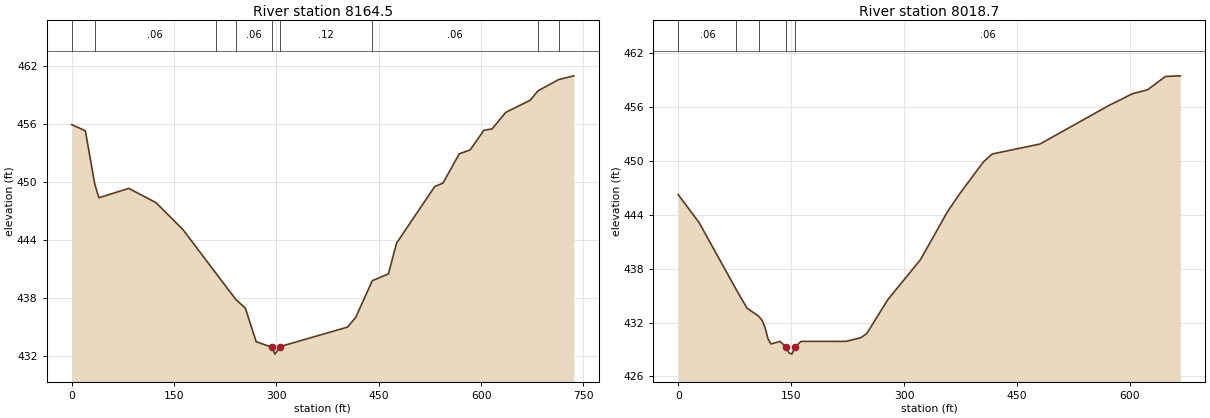
Type RM Length L Ch R = 1 ,8164.5  ,143.7,145.8,147.5
XS GIS Cut Line= 4
     2421445.613      351768.271     2421436.064      352022.611
     2421451.689      352175.389     2421502.905      352499.174
#Sta/Elev= 30
       0  455.92    19.9  455.29   33.73449.7511    39.8  448.35    83.5  449.32
   123.3  447.85     163  445.05  211.06440.5514  240.62437.8036   254.5   436.9
   270.3  433.44   293.6  432.85   297.8  432.15   305.7  432.94   404.2  434.95
   416.1  435.95  440.52439.7589   464.1  440.46     476  443.64     532  449.51
     544  449.86     568   452.9     584  453.31     604  455.34     616  455.48
     636  457.19   671.9  458.45  683.32 459.425  713.84   460.6   735.9  460.98
#Mann= 9 ,-1 , 0
       0    .016       0   33.73     .06       0  211.06    .016       0
  240.62     .06       0   293.6    .045       0   305.7     .12       0
  440.52     .06       0  683.32     .08       0  713.84     .06       0
Bank Sta=293.6,305.7
XS Rating Curve= 0 ,0
Exp/Cntr=0.3,0.1

Type RM Length L Ch R = 1 ,8018.7  ,157.1,151.8,146.4
XS GIS Cut Line= 3
     2421293.367      351904.292     2421298.575      352210.281
     2421486.075      352518.875
#Sta/Elev= 30
       0  446.26    27.8  443.14   77.28435.6508    91.4  433.61  106.79432.7244
   111.3  432.27   115.3  431.48   119.2  430.21   123.2  429.62   135.1  429.91
   143.1   429.3   147.1  428.63     151  428.49     155  429.24     163  429.91
   222.6  429.91   242.4  430.31   250.4  430.77   278.2  434.53   321.9  439.02
   357.6  444.34   373.5   446.3   405.2  449.88   417.1  450.79   480.6   451.9
   571.9  456.18   603.6  457.51   623.5  457.94   647.3  459.43   667.1   459.5
#Mann= 5 ,-1 , 0
       0     .06       0   77.28    .016       0  106.79     .06       0
   143.1    .045       0     155     .06       0
Bank Sta=143.1,155
XS Rating Curve= 0 ,0
Exp/Cntr=0.3,0.1