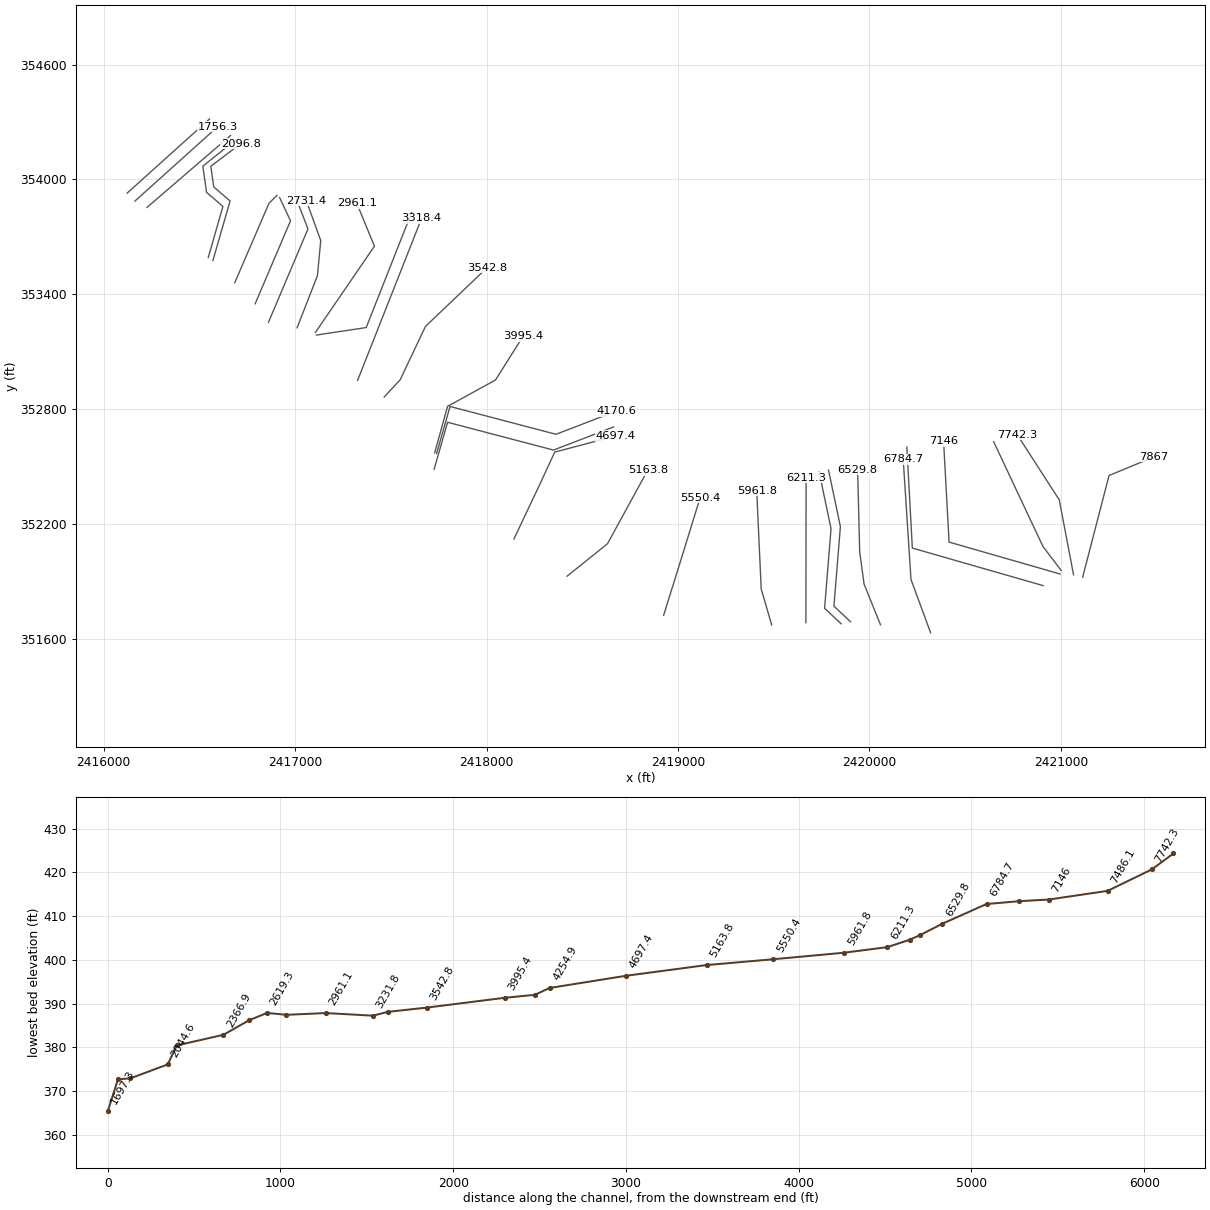
HEC-RAS study OPQNTRIB2.prj: OPQNTRIB2

--- OPQNTRIB2.g01 (geometry) --- (continued)

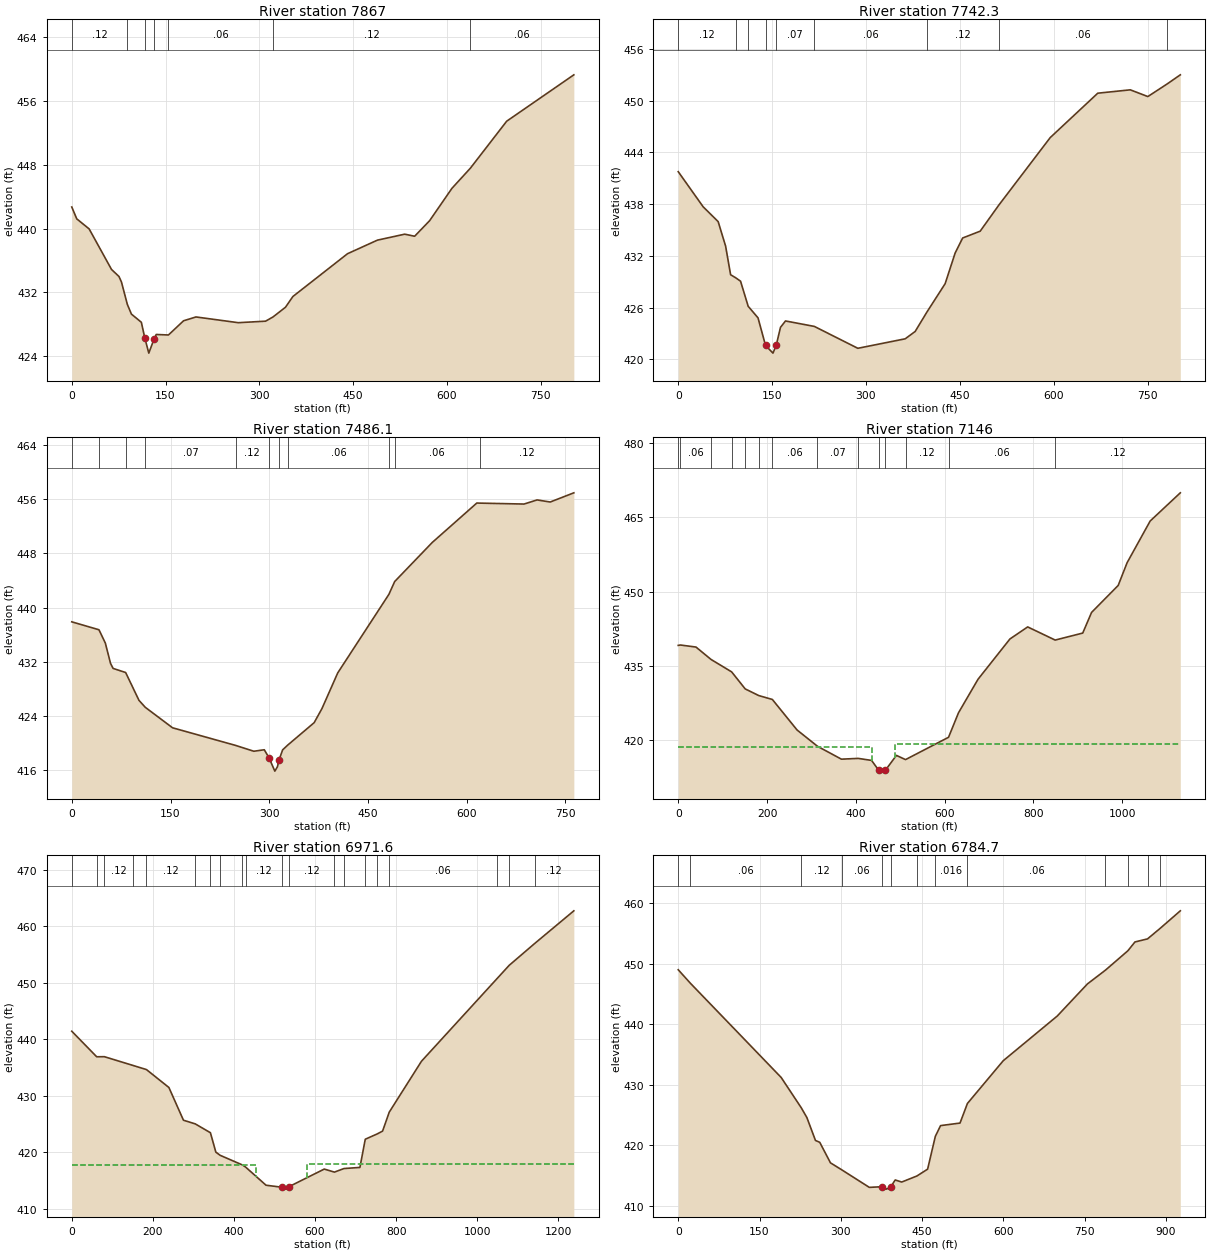
Type RM Length L Ch R = 1 ,7867    ,114.4,124.7,134.7
XS GIS Cut Line= 3
     2421114.016      351922.785     2421251.688      352453.641
     2421486.893       352551.13
#Sta/Elev= 30
       0   442.7       8  441.21    27.8  439.95    63.6  434.86    75.5  433.98
    79.5  433.28   88.89430.4752    95.4  429.26   111.3  428.23   116.7   426.3
   123.2  424.36   131.7  426.15   135.1   426.7  154.62426.6367   178.8  428.42
   198.7   428.9   266.3  428.18     310  428.37  322.09428.9128   341.8  430.12
   353.7  431.47   441.1  436.84   488.8  438.54   532.5  439.29   548.4  439.03
   572.3  440.98   608.1  445.05  637.54447.5745   695.6  453.47     803  459.29
#Mann= 7 ,-1 , 0
       0     .12       0   88.89    .016       0   116.7    .045       0
   131.7     .12       0  154.62     .06       0  322.09     .12       0
  637.54     .06       0
Bank Sta=116.7,131.7
XS Rating Curve= 0 ,0
Exp/Cntr=0.3,0.1

Type RM Length L Ch R = 1 ,7742.3  ,250,256.2,261.4
XS GIS Cut Line= 3
     2421066.273      351934.937      2420991.62       352326.43
      2420772.87       352665.84
#Sta/Elev= 30
       0  441.75    39.8  437.68    63.8  435.96    75.7  433.12    83.7   429.8
   91.75 429.449    99.6  429.05  111.77426.1404   127.5   424.8   139.5   421.6
   151.4  420.71  156.61 421.623   163.4   423.7   171.4  424.44  217.51423.8076
     287  421.27   362.7  422.37   378.6  423.22  397.33425.4666   426.5  428.76
   442.5  432.32   454.5  434.06   482.5  434.85  512.14437.8584   594.4   445.7
   670.4  450.85   722.4  451.24   750.4  450.46  781.57451.9351   802.3  452.98
#Mann= 9 ,-1 , 0
       0     .12       0   91.75    .016       0  111.77     .06       0
   139.5    .045       0  156.61     .07       0  217.51     .06       0
  397.33     .12       0  512.14     .06       0  781.57     .12       0
Bank Sta=139.5,156.61
XS Rating Curve= 0 ,0
Exp/Cntr=0.3,0.1

Type RM Length L Ch R = 1 ,7486.1  ,316,340.1,363.2
XS GIS Cut Line= 3
       2421001.7      351957.677     2420906.648      352082.677
     2420648.836      352630.854
#Sta/Elev= 30
       0  437.88   41.32436.7087      51  434.74    58.9  431.73    62.8  430.99
   81.86430.3854   102.1  426.27  111.68425.2394   153.1  422.21  248.82419.6058
   276.6  418.74   292.5  418.96   299.8  417.75   308.5   415.8   312.5  416.45
   314.8  417.43   320.4  418.95  328.21419.6591   368.3  422.97   380.2  425.07
   404.1  430.33  481.76441.9357  490.58443.8373   547.6  449.61   615.4  455.45
  619.73455.4368   687.1   455.3     707  455.91   726.9   455.6   762.8  456.96
#Mann= 11 ,-1 , 0
       0     .12       0   41.32    .016       0   81.86     .12       0
  111.68     .07       0  248.82     .12       0   299.8    .045       0
   314.8     .12       0  328.21     .06       0  481.76     .12       0
  490.58     .06       0  619.73     .12       0
Bank Sta=299.8,314.8
XS Rating Curve= 0 ,0
Exp/Cntr=0.3,0.1

Type RM Length L Ch R = 1 ,7146    ,121.1,174.4,186.9
XS GIS Cut Line= 3
      2420995.96      351939.278     2420416.099      352105.944
     2420387.453      352632.854
#Sta/Elev= 30
       0  439.16    4.81439.2338      40  438.82   73.92436.3235  120.32433.8179
  150.88430.3873  181.47429.0433  212.01428.2611   267.7  422.11  313.65  418.83
   367.6  416.23   405.4416.3855   435.5  415.98   451.4  414.02   455.5  413.82
   466.4  413.97   491.5  416.99  512.02416.1422  608.93420.6412   631.3  425.57
   675.3  432.33   747.2  440.45   787.2  442.88  849.12440.2296   911.2  441.64
   931.1   445.8   991.1  451.24  1011.1  455.81  1063.1  464.22    1131   469.9
#Mann= 14 ,-1 , 0
       0     .12       0    4.81     .06       0   73.92    .016       0
  120.32     .12       0  150.88     .06       0  181.47     .08       0
  212.01     .06       0  313.65     .07       0   405.4     .06       0
   451.4    .045       0   466.4     .06       0  512.02     .12       0
  608.93     .06       0  849.12     .12       0
#XS Ineff= 2 , 0
          437.15  418.72  487.93          419.22
Permanent Ineff=
       F       F
Bank Sta=451.4,466.4
XS Rating Curve= 0 ,0
Exp/Cntr=0.3,0.1

Type RM Length L Ch R = 1 ,6971.6  ,273.7,186.8,136.3
XS GIS Cut Line= 3
     2420907.419      351878.514     2420224.259      352074.694
     2420195.613      352601.604
#Sta/Elev= 30
       0  441.38   61.49436.8567   80.45436.8713  151.92 435.304  184.28434.5897
   239.6  431.42   275.5  425.63  304.74424.9732  342.01423.4147   355.4  419.98
  365.87419.4206  420.93417.7096  428.66417.3433   479.2  414.12   519.1  413.76
   527.1  413.43   535.1  413.84   622.9  416.98  647.93416.4418   671.5417.0742
   710.8  417.27  723.97422.2601  753.56423.2046   766.7   423.7  783.15427.0564
   862.7  436.07 1047.71450.5888 1079.01 453.042 1142.11 456.921  1238.5  462.69
#Mann= 20 ,-1 , 0
       0     .12       0   61.49     .06       0   80.45     .12       0
  151.92     .06       0  184.28     .12       0  304.74    .016       0
  342.01     .08       0  365.87     .12       0  420.93    .016       0
  428.66     .12       0   519.1    .045       0   535.1     .12       0
  647.93     .08       0   671.5     .12       0  723.97    .016       0
  753.56     .08       0  783.15     .06       0 1047.71     .12       0
 1079.01     .08       0 1142.11     .12       0
#XS Ineff= 2 , 0
          455.11   417.7   580.8           417.8
Permanent Ineff=
       F       F
Bank Sta=519.1,535.1
XS Rating Curve= 0 ,0
Exp/Cntr=0.3,0.1

Type RM Length L Ch R = 1 ,6784.7  ,253.3,255,256.5
XS GIS Cut Line= 3
     2420319.658      351632.246     2420217.228      351910.892
     2420176.429      352539.364
#Sta/Elev= 30
       0  449.02   22.21446.8111     190  431.23   227.3426.1945   237.5   424.6
   253.3  420.83   261.2  420.52     281  417.13  301.57415.9925   352.7  413.08
   376.6  413.19   384.6  412.79   392.5  413.22   400.5   414.3   412.5  413.96
  440.52414.9594   460.3  416.09  474.53421.5048   484.2  423.28   520.1   423.7
  533.75426.9325   599.8  433.99   699.5  441.37   755.3  446.68  788.52448.9525
  829.85452.1474     843  453.61  866.19454.1156  890.05455.8969   926.7  458.75
#Mann= 13 ,-1 , 0
       0     .12       0   22.21     .06       0   227.3     .12       0
  301.57     .06       0   376.6    .045       0   392.5     .06       0
  440.52     .12       0  474.53    .016       0  533.75     .06       0
  788.52     .12       0  829.85     .08       0  866.19     .06       0
  890.05     .12       0
Bank Sta=376.6,392.5
XS Rating Curve= 0 ,0
Exp/Cntr=0.3,0.1

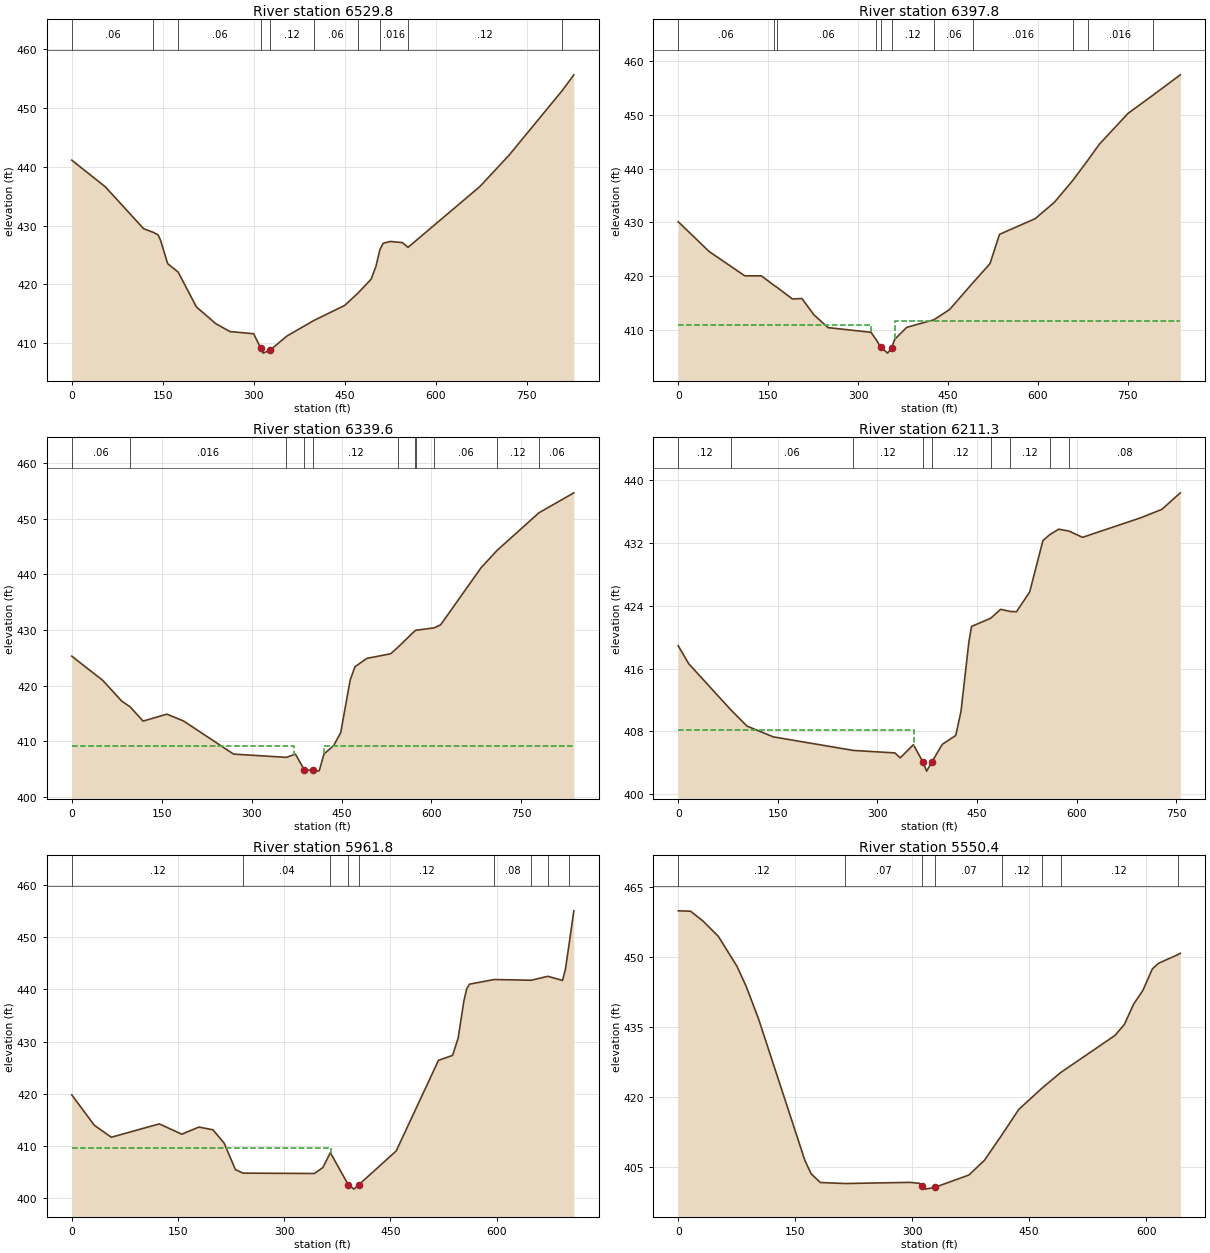
Type RM Length L Ch R = 1 ,6529.8  ,136.9,132,127
XS GIS Cut Line= 4
     2420057.722      351674.347     2419972.002      351887.021
     2419949.215      352054.121     2419938.365      352483.809
#Sta/Elev= 30
       0  441.13    55.4  436.59   118.6  429.46  134.45428.8476   142.3  428.42
   146.3  427.53   158.1  423.53  175.35422.0954   205.6  416.15   237.1  413.34
   260.7  411.97   299.9   411.6   311.7  409.13   315.6   408.3   327.4  408.85
   354.8  411.21  399.14413.8526   449.7   416.4  471.38418.4568   493.5  420.87
   501.4  423.02  508.04425.8948   513.4     427   525.3   427.3   545.2   427.1
  554.43426.2974   672.6  436.62   720.3  441.89  808.91453.0072   827.8  455.65
#Mann= 10 ,-1 , 0
       0     .06       0  134.45     .12       0  175.35     .06       0
   311.7    .045       0   327.4     .12       0  399.14     .06       0
  471.38     .12       0  508.04    .016       0  554.43     .12       0
  808.91     .06       0
Bank Sta=311.7,327.4
XS Rating Curve= 0 ,0
Exp/Cntr=0.3,0.1

Type RM Length L Ch R = 1 ,6397.8  ,51.5,58.1,62
XS GIS Cut Line= 4
     2419901.563      351689.719     2419814.757      351771.099
     2419848.394      352186.681     2419786.545       352481.82
#Sta/Elev= 30
       0  430.11    51.6  424.56     111  420.04   138.8  420.03  160.15418.2321
  164.21  417.94   190.5  415.73   206.4  415.81   226.2  412.78     250  410.39
   321.5  409.52  330.49408.1039   337.4  406.79   349.3  405.64  355.93 406.609
   361.2  408.23   381.1  410.44  426.37411.8503   452.5  413.74  491.78418.7754
     520   422.3   535.9  427.76   595.4  430.68   627.2   433.7  658.31437.8259
  683.11441.5435   702.6  444.57   750.2  450.28  791.66453.6628   837.5  457.47
#Mann= 11 ,-1 , 0
       0     .06       0  160.15     .12       0  164.21     .06       0
  330.49     .12       0   337.4    .045       0  355.93     .12       0
  426.37     .06       0  491.78    .016       0  658.31     .12       0
  683.11    .016       0  791.66     .06       0
#XS Ineff= 2 , 0
          321.98  410.84   361.2          411.66
Permanent Ineff=
       F       F
Bank Sta=337.4,355.93
XS Rating Curve= 0 ,0
Exp/Cntr=0.3,0.1

Type RM Length L Ch R = 1 ,6339.6  ,132.7,128.3,126.1
XS GIS Cut Line= 4
     2419852.735      351678.868     2419765.929      351760.248
     2419799.566       352175.83     2419737.717      352470.969
#Sta/Elev= 30
       0  425.29    51.6  420.95    83.3  417.22   97.35416.1851     119  413.62
   158.7  414.87   186.5  413.64   269.9  407.69  357.86407.1049   373.1  407.68
   388.2  404.82   403.2   404.8   408.9  404.63   412.8  404.71   420.8  407.72
   436.7   409.2   448.6  411.54   464.4     421   472.4  423.39   492.2  424.89
     532  425.72  543.75426.8557  571.87429.7896  574.02429.9454  604.28430.3668
   615.3  430.92   682.7  441.17  709.77444.3288   779.1451.0356   837.5  454.64
#Mann= 11 ,-1 , 0
       0     .06       0   97.35    .016       0  357.86     .12       0
   388.2    .045       0   403.2     .12       0  543.75     .08       0
  571.87     .12       0  574.02    .016       0  604.28     .06       0
  709.77     .12       0   779.1     .06       0
#XS Ineff= 2 , 0
          370.49  409.22  421.05          409.12
Permanent Ineff=
       F       F
Bank Sta=388.2,403.2
XS Rating Curve= 0 ,0
Exp/Cntr=0.3,0.1

Type RM Length L Ch R = 1 ,6211.3  ,248.5,249.4,250.4
XS GIS Cut Line= 2
     2419668.273      351685.379     2419669.358      352441.672
#Sta/Elev= 30
       0   418.9    15.9  416.61   79.01410.7682   103.5  408.68   143.3   407.3
  263.93405.5754   326.4  405.26   334.4  404.63   354.3  406.31  368.22404.1541
   374.2  402.94   382.1  404.13     398  406.37     418  407.48   425.9  410.53
   437.8   419.4   441.8  421.37  470.74422.4176   485.6  423.55  500.25423.2773
   509.5  423.24   529.4  425.76   549.3   432.3  559.28433.0409   573.2  433.76
   588.8 433.512     609  432.72   696.6  435.21   728.4  436.28   756.3  438.39
#Mann= 9 ,-1 , 0
       0     .12       0   79.01     .06       0  263.93     .12       0
  368.22    .045       0   382.1     .12       0  470.74     .06       0
  500.25     .12       0  559.28    .016       0   588.8     .08       0
#XS Ineff= 2 , 0
          355.01  408.24
Permanent Ineff=
       F       F
Bank Sta=368.22,382.1
XS Rating Curve= 0 ,0
Exp/Cntr=0.3,0.1

Type RM Length L Ch R = 1 ,5961.8  ,419.2,411.5,403.5
XS GIS Cut Line= 3
     2419489.497      351673.526     2419434.809      351861.026
     2419411.372      352374.047
#Sta/Elev= 30
       0  419.76    31.9  413.92    55.8  411.63   123.6  414.19   155.4  412.21
   179.4  413.58   199.3  413.06   215.2  410.49   231.1  405.41  241.84  404.74
   342.6  404.67   354.6  405.82  365.11408.6748   390.4  402.51   398.4  401.67
  405.06402.4876   458.1     409   517.8  426.39   537.7  427.34   545.6  430.68
   553.6  437.76   557.6   440.1   561.6  441.01  596.51441.8955  648.92441.7576
  672.24442.5159   692.9  441.72   696.9  443.79  701.81448.3068   708.9  455.08
#Mann= 9 ,-1 , 0
       0     .12       0  241.84     .04       0  365.11     .12       0
   390.4    .045       0  405.06     .12       0  596.51     .08       0
  648.92    .016       0  672.24     .08       0  701.81     .06       0
#XS Ineff= 2 , 0
          366.56  409.53
Permanent Ineff=
       F       F
Bank Sta=390.4,405.06
XS Rating Curve= 0 ,0
Exp/Cntr=0.3,0.1

Type RM Length L Ch R = 1 ,5550.4  ,391.5,386.6,381.5
XS GIS Cut Line= 3
     2418925.284      351723.843     2419019.664      352026.407
     2419116.079      352338.573
#Sta/Elev= 30
       0  459.87    15.8  459.79    31.7  457.69    51.5  454.38    75.3  447.98
    87.2  443.64     103  436.68   162.4  406.32   170.4  403.46   182.2  401.59
  214.14 401.373   297.1  401.62     309  401.42     313  400.75   316.9  400.17
   328.9  400.55   372.7   403.2   392.6  406.36  415.05411.8368   436.5  417.25
  466.16421.8024  490.24 425.169     560  433.15   571.9  435.48   583.9  439.87
   595.8  442.82   607.8   447.4   615.8  448.62   640.6450.4755   643.7  450.77
#Mann= 8 ,-1 , 0
       0     .12       0  214.14     .07       0     313    .045       0
   328.9     .07       0  415.05     .12       0  466.16     .06       0
  490.24     .12       0   640.6     .08       0
Bank Sta=313,328.9
XS Rating Curve= 0 ,0
Exp/Cntr=0.3,0.1

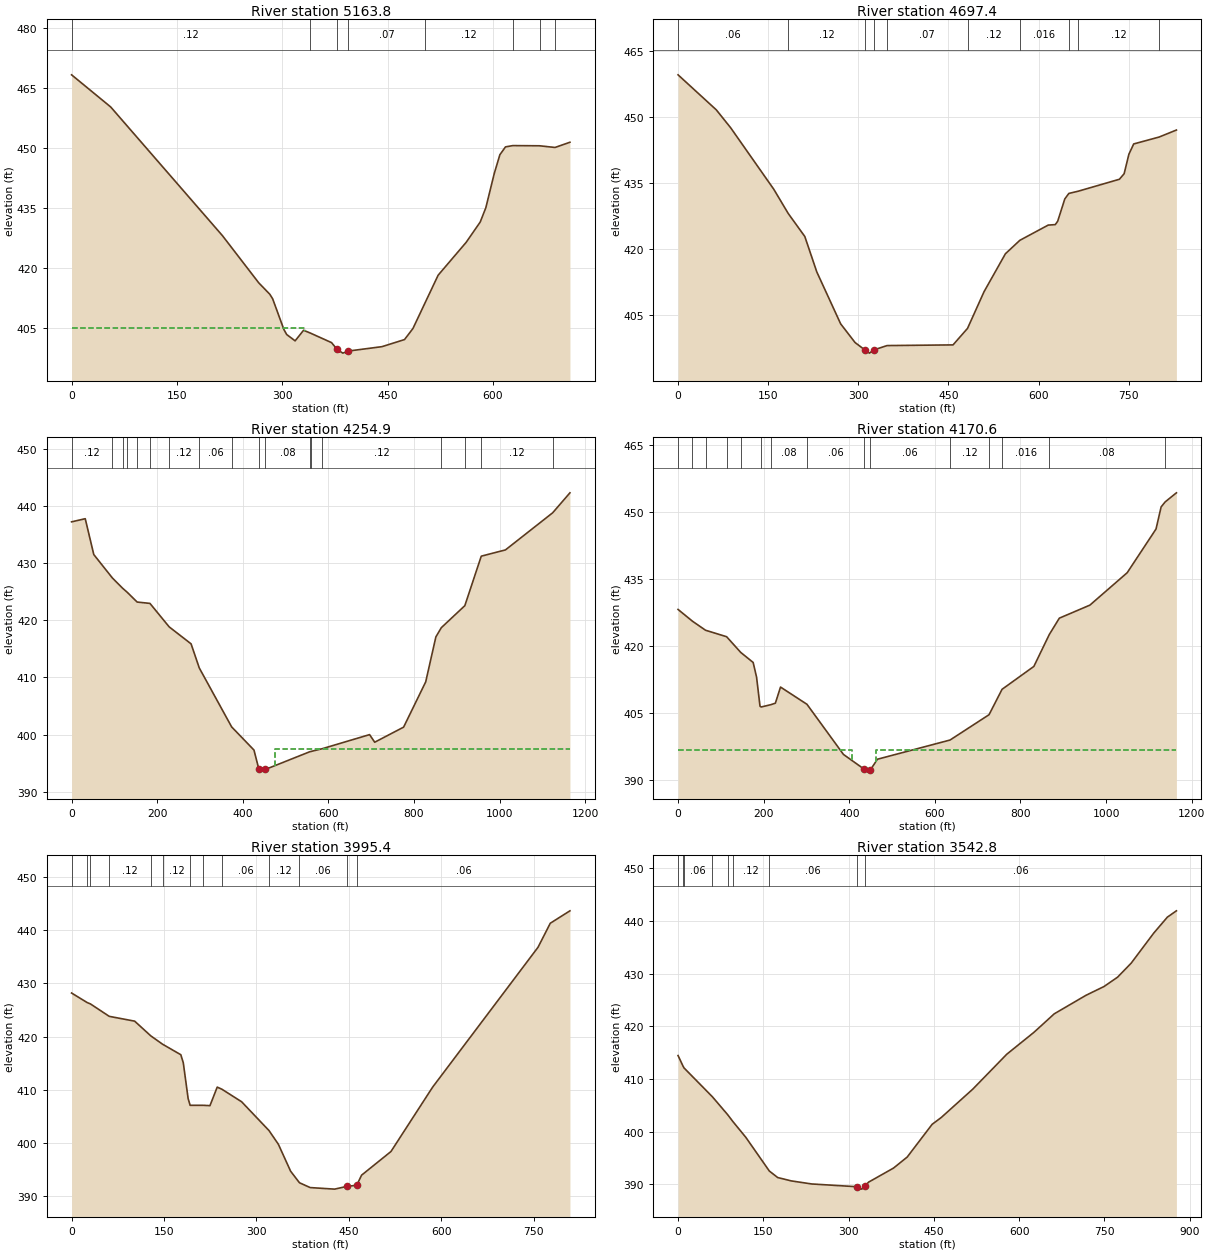
Type RM Length L Ch R = 1 ,5163.8  ,464.6,466.4,467.9
XS GIS Cut Line= 3
      2418420.92      351927.867     2418631.858      352097.137
     2418842.795      352482.554
#Sta/Elev= 30
       0  468.39    55.7  460.36   214.8  428.21   266.5  416.42   282.4  413.54
   286.4  412.41   302.4  404.74   306.4  403.49   318.4  401.91   330.4  404.55
  340.01403.8594   370.3  401.46   378.3  399.75   386.3  398.84   394.3  399.36
   442.2  400.46   474.2  402.23   486.2     405  503.57411.4492   522.1  418.32
     562  426.53     582   431.6     590  435.17     602  443.73     610  448.42
     618  450.38  628.35450.7018   666.6450.6555  688.53450.2377   709.8  451.54
#Mann= 8 ,-1 , 0
       0     .12       0  340.01     .07       0   378.3    .045       0
   394.3     .07       0  503.57     .12       0  628.35     .06       0
   666.6     .08       0  688.53    .016       0
#XS Ineff= 2 , 0
          331.89  405.14
Permanent Ineff=
       F       F
Bank Sta=378.3,394.3
XS Rating Curve= 0 ,0
Exp/Cntr=0.3,0.1

Type RM Length L Ch R = 1 ,4697.4  ,474.4,442.5,410
XS GIS Cut Line= 4
     2418143.051      352121.946     2418279.478       352409.77
     2418356.132      352575.855     2418673.264      352659.771
#Sta/Elev= 30
       0   459.6    63.7  451.64    87.6  447.57   159.3  433.62  183.34428.1195
     211  422.88   230.9  414.85   270.7  403.03   294.6   398.8     311  397.11
   318.5  396.39     326  397.13  347.91398.1049   457.7  398.26  481.83402.0096
   509.4  410.36   544.9  418.96  568.89422.0083   616.1  425.47   627.9  425.58
   631.9  426.35   643.7   431.4  650.45432.6598  666.18433.1706   734.6  435.88
   742.5  437.14   750.4  441.56   758.4   443.9  800.66445.4665   829.5  447.06
#Mann= 10 ,-1 , 0
       0     .06       0  183.34     .12       0     311    .045       0
     326     .12       0  347.91     .07       0  481.83     .12       0
  568.89    .016       0  650.45     .08       0  666.18     .12       0
  800.66     .06       0
Bank Sta=311,326
XS Rating Curve= 0 ,0
Exp/Cntr=0.3,0.1

Type RM Length L Ch R = 1 ,4254.9  ,92,84.3,84.4
XS GIS Cut Line= 4
     2417726.404      352486.359     2417796.567       352731.85
     2418349.806      352586.537     2418664.354       352707.45
#Sta/Elev= 30
       0  437.24    31.9  437.79    51.9  431.51   95.44427.4052  119.26425.6174
  130.41424.8802  153.17423.1987  183.09422.9638  228.02418.8527   279.2  415.88
  298.31411.6642  373.96401.3416   426.1  397.29   437.6  393.93     442   393.6
   452.6  393.89  556.27396.9877  559.57397.0493  585.57397.5229   696.2  399.99
   708.2  398.66   775.7   401.3   827.3  409.22   851.1   417.1  863.86418.7159
  918.72422.5659  957.14431.2307  1013.7  432.33 1123.98 438.826  1164.3  442.32
#Mann= 18 ,-1 , 0
       0     .12       0   95.44     .06       0  119.26     .08       0
  130.41     .06       0  153.17     .12       0  183.09     .06       0
  228.02     .12       0  298.31     .06       0  373.96     .12       0
   437.6    .045       0   452.6     .08       0  556.27     .12       0
  559.57     .08       0  585.57     .12       0  863.86    .016       0
  918.72     .08       0  957.14     .12       0 1123.98     .06       0
#XS Ineff= 2 , 0
                          475.54           397.4
Permanent Ineff=
       F       F
Bank Sta=437.6,452.6
XS Rating Curve= 0 ,0
Exp/Cntr=0.3,0.1

Type RM Length L Ch R = 1 ,4170.6  ,137.6,175.2,202.4
XS GIS Cut Line= 4
     2417739.425      352568.824     2417809.588      352814.315
     2418362.827      352669.002     2418677.375      352789.915
#Sta/Elev= 30
       0   428.2   33.68425.5676   64.23423.5488   113.5   422.1  146.47418.5858
   175.5  416.34   183.5  413.03   191.5  406.55  194.25 406.385     217 406.904
   227.4  407.24   239.4  410.84   301.2 406.985   386.4  395.78   433.9  392.54
     446  392.04   448.9  392.26   465.8   394.7  635.43398.9933  726.58 404.657
  756.97410.3377   831.3  415.46  867.29 422.585   890.8  426.25   962.1  429.16
  1049.3  436.41  1116.7  446.19  1128.6  451.13 1138.23452.2663  1164.3  454.28
#Mann= 15 ,-1 , 0
       0     .12       0   33.68     .08       0   64.23     .12       0
   113.5     .06       0  146.47     .12       0  194.25    .016       0
     217     .08       0   301.2     .06       0   433.9    .045       0
   448.9     .06       0  635.43     .12       0  726.58     .08       0
  756.97    .016       0  867.29     .08       0 1138.23     .12       0
#XS Ineff= 2 , 0
          407.43  396.74  461.92          396.74
Permanent Ineff=
       F       F
Bank Sta=433.9,448.9
XS Rating Curve= 0 ,0
Exp/Cntr=0.3,0.1

Type RM Length L Ch R = 1 ,3995.4  ,401.4,452.5,469.7
XS GIS Cut Line= 4
     2417729.254       352571.88     2417796.528      352814.936
     2418047.179       352952.74     2418191.493      353181.689
#Sta/Elev= 30
       0  428.17   25.47426.3719   30.62426.1232   61.11 423.793   102.4  422.89
  128.67420.1196  147.87418.5483   177.3  416.59   181.3  415.09   189.2  408.35
  192.42 407.095  213.54407.0947   224.6  407.03   236.4  410.51  244.02410.1087
     276  407.76  320.44402.3553   335.6  399.79   355.5  394.73  369.89392.5559
   387.3  391.65     427  391.36   446.9  391.88   462.8  392.08   470.7  393.98
   518.4  398.42     586   410.5   757.1  436.76     777  441.27   808.9   443.6
#Mann= 13 ,-1 , 0
       0     .12       0   25.47     .06       0   30.62     .08       0
   61.11     .12       0  128.67     .06       0  147.87     .12       0
  192.42    .016       0  213.54     .08       0  244.02     .06       0
  320.44     .12       0  369.89     .06       0   446.9    .045       0
   462.8     .06       0
Bank Sta=446.9,462.8
XS Rating Curve= 0 ,0
Exp/Cntr=0.3,0.1

Type RM Length L Ch R = 1 ,3542.8  ,221.8,224.4,227
XS GIS Cut Line= 4
     2417465.582      352863.764     2417549.341      352954.297
     2417681.078      353232.379     2418003.776      353539.762
#Sta/Elev= 30
       0  414.48    8.52412.5247   10.44412.1357   60.49 406.639   87.17 403.264
   97.03401.8711   119.4  398.92  160.58392.5492   175.3  391.31   199.3  390.67
   235.2  390.09     314  389.57   323.2  389.11     329  389.69   335.1  390.43
   379.1  393.11   403.1   395.2     447  401.42   462.9   402.7   518.6  408.11
   578.3  414.73     626  418.88   661.8   422.4   717.5  425.91   749.4  427.59
   773.2  429.36   797.1  432.02   836.9  437.74   860.8  440.76   876.7  441.96
#Mann= 9 ,-1 , 0
       0    .016       0    8.52     .08       0   10.44     .06       0
   60.49     .12       0   87.17     .06       0   97.03     .12       0
  160.58     .06       0     314    .045       0     329     .06       0
Bank Sta=314,329
XS Rating Curve= 0 ,0
Exp/Cntr=0.3,0.1

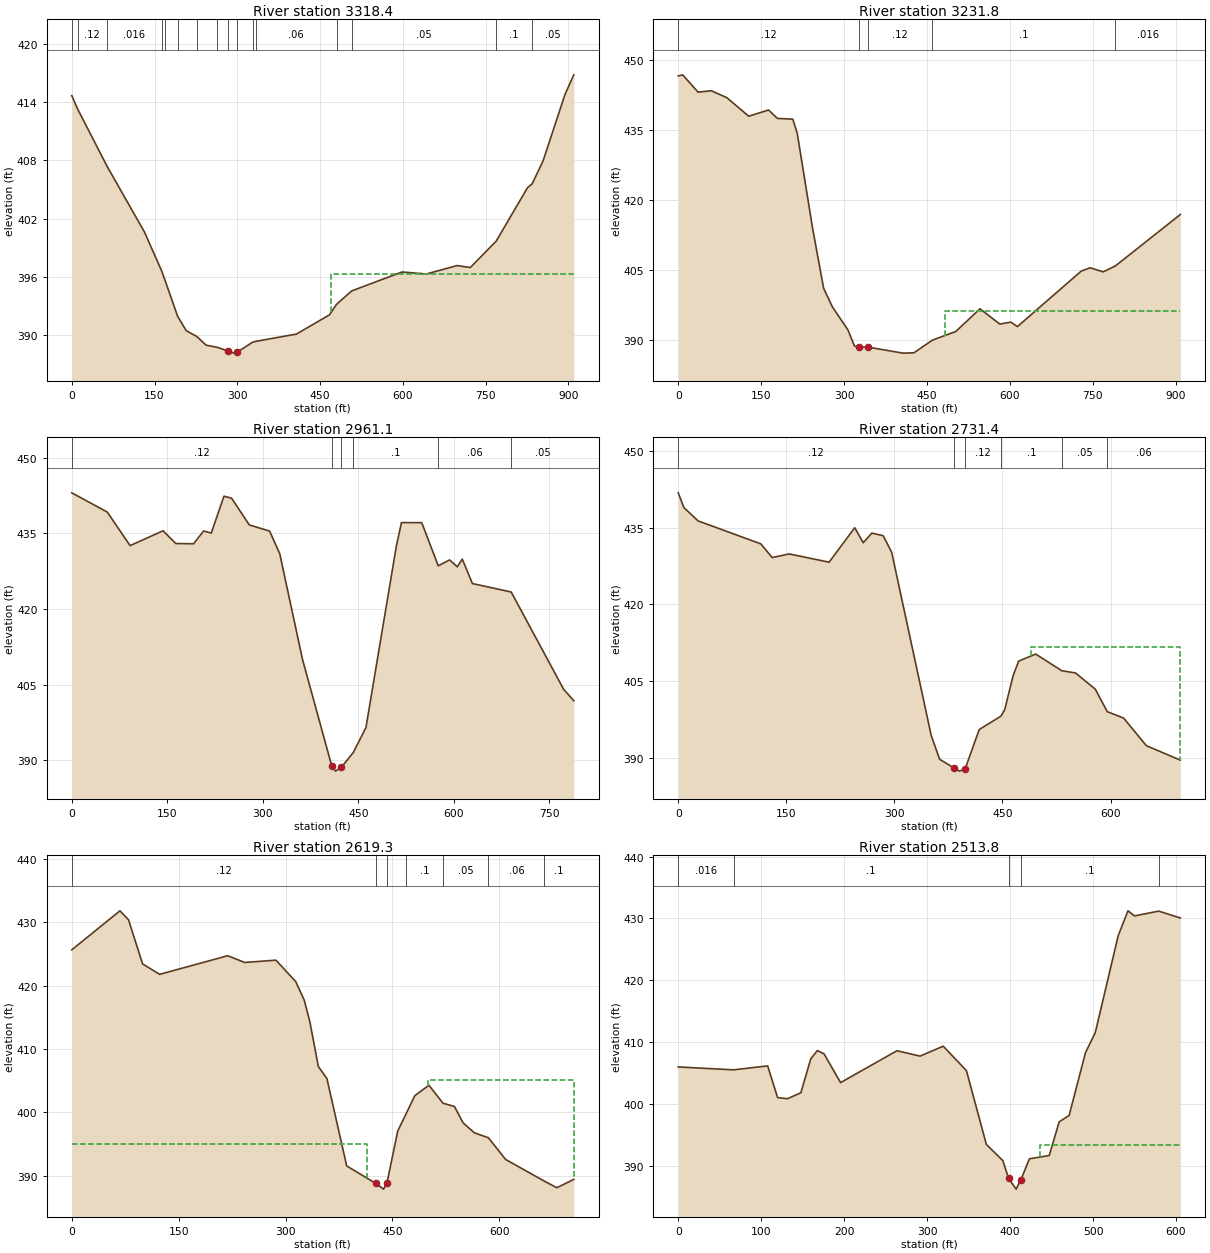
Type RM Length L Ch R = 1 ,3318.4  ,70.9,86.6,112.5
XS GIS Cut Line= 2
     2417326.693       352950.57     2417660.894      353796.924
#Sta/Elev= 30
       0  414.67   10.44413.3099   63.78407.4108   131.7  400.62  163.32396.5627
  169.78395.5258  191.82391.9453   207.5  390.45  226.73389.8508   243.4  388.96
  263.83388.7385   283.4  388.35   294.1  388.14   299.3  388.22  327.91 389.271
  333.74389.3554   407.1   390.1     467  392.08  480.09393.1782  507.28394.5475
   598.6   396.5   642.6  396.29   698.4  397.16   722.4  396.96  769.29399.6791
   826.1  405.19  834.45405.5828   854.1  407.92     894   414.8     910  416.81
#Mann= 16 ,-1 , 0
       0     .06       0   10.44     .12       0   63.78    .016       0
  163.32     .12       0  169.78     .06       0  191.82    .016       0
  226.73     .06       0  263.83     .12       0   283.4    .045       0
   299.3     .12       0  327.91    .016       0  333.74     .06       0
  480.09    .016       0  507.28     .05       0  769.29      .1       0
  834.45     .05       0
#XS Ineff= 2 , 0
                          470.59          396.29
Permanent Ineff=
       F       F
Bank Sta=283.4,299.3
XS Rating Curve= 0 ,0
Exp/Cntr=0.3,0.1

Type RM Length L Ch R = 1 ,3231.8  ,292.3,270.7,238.2
XS GIS Cut Line= 3
     2417111.524      353187.332     2417371.599      353226.529
     2417608.486      353826.438
#Sta/Elev= 30
       0  446.68       8  446.92    35.9  443.21    59.8  443.51    87.7  442.04
   127.5  438.05   163.4  439.38   179.3  437.58   207.2  437.42   215.2   434.4
   243.1  413.94     263  401.15   278.9  397.16   306.8  392.27   318.8  388.76
   327.3   388.6   342.3  388.58   406.3  387.27   426.2  387.34  459.65390.0497
   501.9   391.9   545.7  396.77   581.5   393.5   601.4  393.92   613.4  392.95
   728.8  404.85   744.8  405.56   768.6  404.69  790.72405.9666     908  416.98
#Mann= 5 ,-1 , 0
       0     .12       0   327.3    .045       0   342.3     .12       0
  459.65      .1       0  790.72    .016       0
#XS Ineff= 2 , 0
                          481.94           396.2
Permanent Ineff=
       F       F
Bank Sta=327.3,342.3
XS Rating Curve= 0 ,0
Exp/Cntr=0.3,0.1

Type RM Length L Ch R = 1 ,2961.1  ,217.9,229.7,240.9
XS GIS Cut Line= 3
     2417106.424      353201.221     2417414.584      353651.525
     2417322.353      353876.134
#Sta/Elev= 30
       0  443.06    55.8  439.24    91.6  432.59   143.4  435.53   163.3  433.01
   191.2  432.95   207.1  435.49   219.1  435.08     239  442.39   250.9  442.01
   278.8   436.7   310.7  435.47   326.6     431   362.4  410.01   408.5   388.8
   414.2  387.87   423.5  388.64     442391.5382     462   396.5   509.8  432.53
   517.8  437.16   549.6  437.14  575.58428.5892   593.4  429.76   605.4  428.38
   613.3  429.92   629.2  425.07  690.12423.3906   772.5  404.09   788.5  401.83
#Mann= 6 ,-1 , 0
       0     .12       0   408.5    .045       0   423.5     .12       0
     442      .1       0  575.58     .06       0  690.12     .05       0
Bank Sta=408.5,423.5
XS Rating Curve= 0 ,0
Exp/Cntr=0.3,0.1

Type RM Length L Ch R = 1 ,2731.4  ,119.1,112.1,105.2
XS GIS Cut Line= 4
     2417010.463      353225.115       2417116.8      353497.467
     2417134.161      353680.844     2417059.291      353888.092
#Sta/Elev= 30
       0  441.79     7.9   438.9    27.7   436.3   114.6  431.83   130.4  429.16
   154.1  429.86   209.4  428.25     245  434.98   256.8  432.05   268.7  433.93
   284.5  433.42   296.3  430.17   351.2   394.4   362.9  389.77   382.5  388.11
   390.4  387.47   398.2  387.89   417.8  395.59  447.88398.1942   453.1  399.42
   464.8  406.08   472.6  408.95   496.2  410.32  532.38 407.067   551.3  406.64
   578.9  403.47  595.52399.0716   618.2  397.83   649.7  392.44   696.9  389.62
#Mann= 6 ,-1 , 0
       0     .12       0   382.5    .045       0   398.2     .12       0
  447.88      .1       0  532.38     .05       0  595.52     .06       0
#XS Ineff= 2 , 0
                          489.06          411.69
Permanent Ineff=
       F       F
Bank Sta=382.5,398.2
XS Rating Curve= 0 ,0
Exp/Cntr=0.3,0.1

Type RM Length L Ch R = 1 ,2619.3  ,105.5,105.5,105.4
XS GIS Cut Line= 3
     2416861.198      353254.389     2417067.361      353741.585
     2417004.427      353905.431
#Sta/Elev= 30
       0  425.68    67.6  431.84    79.6  430.43    99.4  423.46   123.3  421.81
   218.8  424.75   242.6  423.69   286.4  424.05   314.2  420.68   326.2  417.74
   334.1  414.31     346  407.26     358  405.36   385.8  391.56  426.55388.8046
   437.5   387.9   442.2388.8275   457.4  397.08  468.62399.6718   481.3  402.65
   501.2   404.3  520.98401.4584     537  400.95     549  398.38   564.9  396.79
  584.62396.0117   608.8  392.58  663.22389.1563   680.6  388.12   704.5  389.44
#Mann= 7 ,-1 , 0
       0     .12       0  426.55    .045       0   442.2     .12       0
  468.62      .1       0  520.98     .05       0  584.62     .06       0
  663.22      .1       0
#XS Ineff= 2 , 0
          413.62     395  499.48          405.14
Permanent Ineff=
       F       F
Bank Sta=426.55,442.2
XS Rating Curve= 0 ,0
Exp/Cntr=0.3,0.1

Type RM Length L Ch R = 1 ,2513.8  ,146.9,146.8,146.7
XS GIS Cut Line= 3
      2416791.58       353350.61     2416976.216       353784.12
     2416919.317      353905.453
#Sta/Elev= 30
       0  405.97   66.71405.4981   107.8  406.14   119.8     401   131.8  400.83
   147.8  401.79   159.7  407.25   167.7  408.62   175.7   408.1   195.7  403.43
   263.6  408.59   291.5  407.72   319.4  409.33   347.4  405.37   371.4  393.43
   391.3   390.8   398.2  387.94   407.3  386.19   413.2  387.74   423.3   391.1
   447.2  391.63   459.2  397.08   471.2  398.12   490.9  408.28   502.7  411.52
   530.3   427.2   542.1  431.24     550  430.42  579.25431.1917   605.2  430.08
#Mann= 5 ,-1 , 0
       0    .016       0   66.71      .1       0   398.2    .045       0
   413.2      .1       0  579.25    .016       0
#XS Ineff= 2 , 0
                          436.33          393.38
Permanent Ineff=
       F       F
Bank Sta=398.2,413.2
XS Rating Curve= 0 ,0
Exp/Cntr=0.3,0.1

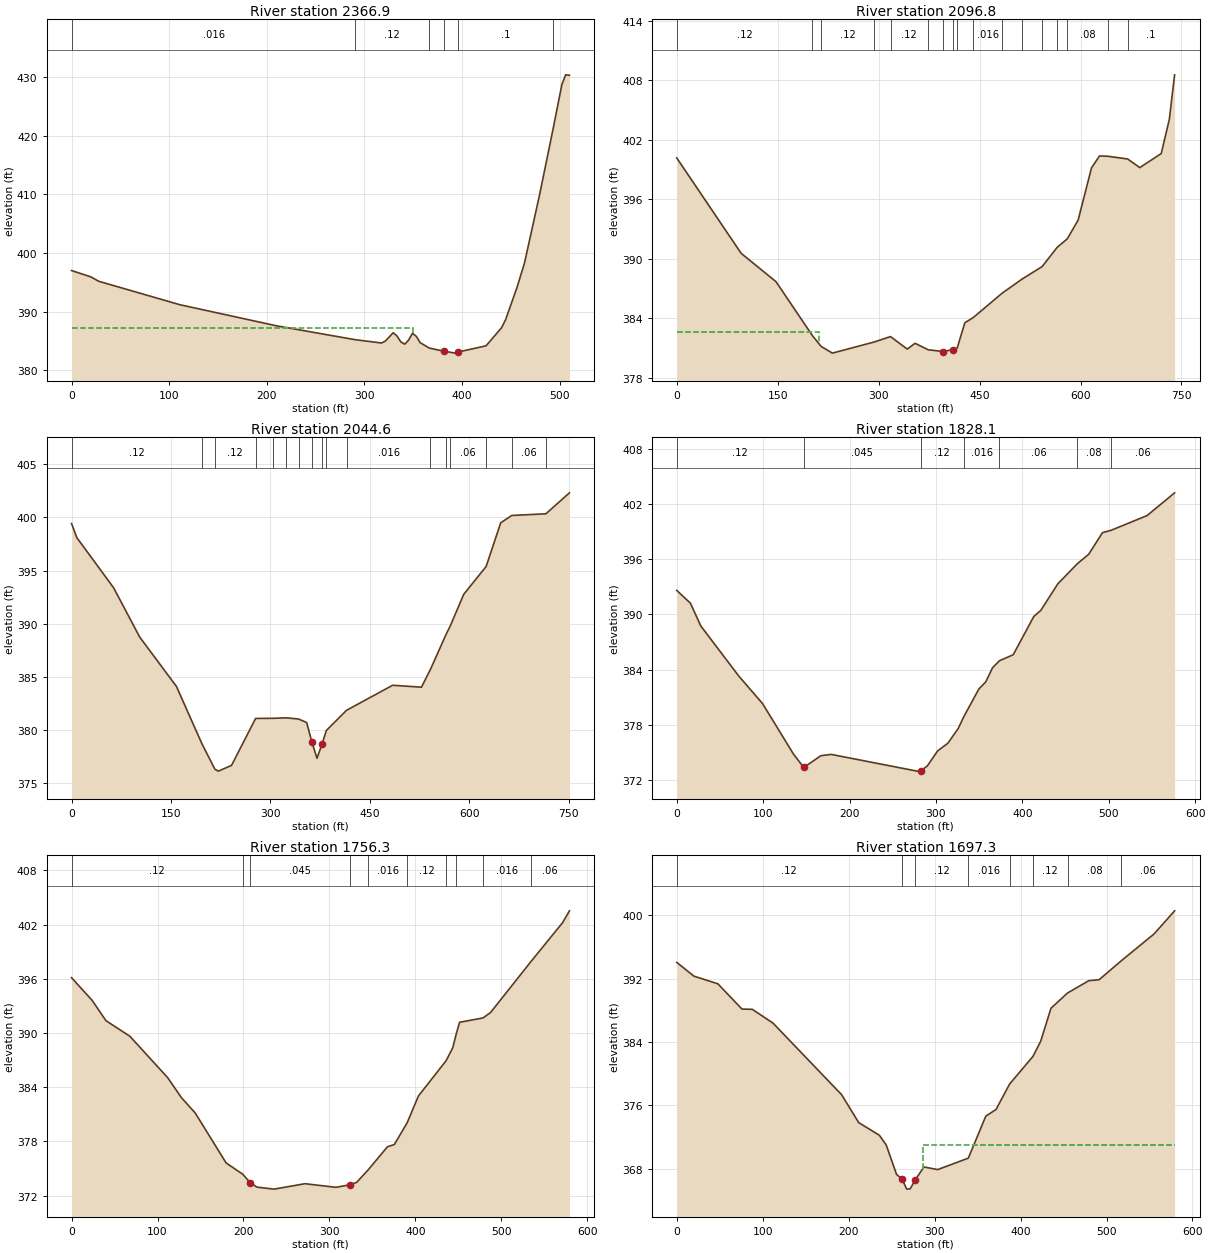
Type RM Length L Ch R = 1 ,2366.9  ,191.2,270.1,302.4
XS GIS Cut Line= 3
     2416684.942      353460.575     2416863.979      353876.156
     2416905.211      353916.304
#Sta/Elev= 30
       0     397    19.8  395.92    27.8  395.17   111.1  391.16   210.4  387.55
   290.9385.1846   317.6  384.63   321.5  384.96   329.5  386.38   333.4  385.83
   337.4  384.81   341.4  384.43   345.3  385.12   349.3  386.29   353.3  385.75
   357.2  384.68  366.42383.7659   381.3  383.24     393   382.9   396.3   383.1
   424.7  384.15   440.6  387.25   444.6  388.57   456.3  394.08     464  398.25
   479.4  409.86  493.42421.2486   502.4   428.8   506.2  430.42   510.1  430.34
#Mann= 6 ,-1 , 0
       0    .016       0   290.9     .12       0  366.42      .1       0
   381.3    .045       0   396.3      .1       0  493.42    .016       0
#XS Ineff= 2 , 0
          349.85   387.2
Permanent Ineff=
       F       F
Bank Sta=381.3,396.3
XS Rating Curve= 0 ,0
Exp/Cntr=0.3,0.1

Type RM Length L Ch R = 1 ,2096.8  ,101,52.3,46.1
XS GIS Cut Line= 5
     2416571.053      353577.155     2416660.637      353887.571
      2416575.22      353961.183     2416559.942      354068.821
     2416715.498      354186.877
#Sta/Elev= 30
       0  400.16    95.7  390.54   147.6  387.67   201.7382.2275  214.61 381.144
   231.3  380.47  293.43381.5936  317.65382.1381   342.5  380.88   354.2  381.46
  373.62380.8102     396  380.63     411  380.83  416.67380.9748   428.1  383.53
  440.56384.0553  483.18 386.498  513.06387.9352  542.94389.1987  565.31391.1406
  580.25391.9914   596.4  393.88   616.3  399.15   628.2  400.36  640.37400.3279
     670400.0525     688  399.18   719.9   400.6   731.9  404.03   739.8  408.54
#Mann= 17 ,-1 , 0
       0     .12       0   201.7     .06       0  214.61     .12       0
  293.43    .016       0  317.65     .12       0  373.62    .016       0
     396    .045       0     411    .016       0  416.67     .12       0
  440.56    .016       0  483.18     .12       0  513.06     .06       0
  542.94     .12       0  565.31     .06       0  580.25     .08       0
  640.37     .06       0     670      .1       0
#XS Ineff= 2 , 0
          211.35  382.58
Permanent Ineff=
       F       F
Bank Sta=396,411
XS Rating Curve= 0 ,0
Exp/Cntr=0.3,0.1

Type RM Length L Ch R = 1 ,2044.6  ,257.9,216.4,174.4
XS GIS Cut Line= 5
     2416546.788      353592.797     2416623.137      353859.099
      2416537.72       353932.71     2416518.276      354069.516
     2416692.581      354209.099
#Sta/Elev= 30
       0  399.43     7.9  398.11    63.3   393.4   102.9  388.74   158.3   384.1
  196.78378.6988  216.39376.3021   221.6  376.13   241.4  376.67  277.75  381.09
  304.15381.0991  323.85381.1446  342.56381.0337   354.8   380.7   362.6  378.87
   370.4  377.34   378.1378.7065  384.42 379.951  414.95381.8544   484.5  384.21
     528  384.03  541.56385.7047  564.95388.9685  571.72 389.829   591.8  392.77
  625.59 395.389   647.6   399.5  664.24 400.188  715.79400.3466   751.3  402.32
#Mann= 17 ,-1 , 0
       0     .12       0  196.78     .06       0  216.39     .12       0
  277.75    .016       0  304.15     .06       0  323.85    .016       0
  342.56     .06       0   362.6    .045       0   378.1    .016       0
  384.42     .12       0  414.95    .016       0  541.56     .06       0
  564.95     .12       0  571.72     .06       0  625.59     .08       0
  664.24     .06       0  715.79      .1       0
Bank Sta=362.6,378.1
XS Rating Curve= 0 ,0
Exp/Cntr=0.3,0.1

Type RM Length L Ch R = 1 ,1828.1  ,71.3,71.9,72.4
XS GIS Cut Line= 2
     2416226.297      353853.882     2416663.199      354229.663
#Sta/Elev= 30
       0  392.61    15.9  391.21    27.8  388.75    71.5  383.33    99.4  380.29
   135.1  374.81     147  373.35   166.9  374.63   178.8  374.77   278.2  372.95
   282.2  372.96   290.1  373.52     302  375.15     314     376   325.9   377.6
  332.04 378.826   349.7  381.88   357.7  382.66   365.6   384.2  373.57 384.958
   389.5  385.61   413.3  389.77   421.3  390.42   441.2  393.33  463.52395.4927
   476.9  396.54   492.8  398.89  503.02399.1526   544.5  400.75   576.3  403.22
#Mann= 7 ,-1 , 0
       0     .12       0     147    .045       0   282.2     .12       0
  332.04    .016       0  373.57     .06       0  463.52     .08       0
  503.02     .06       0
Bank Sta=147,282.2
XS Rating Curve= 0 ,0
Exp/Cntr=0.3,0.1

Type RM Length L Ch R = 1 ,1756.3  ,59,59,59
XS GIS Cut Line= 2
     2416163.678      353887.127     2416594.307      354274.543
#Sta/Elev= 30
       0  396.13      24  393.61      40  391.37    67.9  389.64   111.9  385.05
   127.8  382.85   143.8  381.16   179.8  375.62  199.07374.3752   207.7  373.45
   215.7  372.94   235.7  372.72   271.6  373.32   307.6  372.92   323.6   373.2
   331.6  373.46  345.35374.8856   367.5  377.41   375.5  377.66  390.38  380.06
   403.5  383.03  435.83386.9513   443.4  388.36  447.38389.8525   451.4  391.19
  478.67391.6727   487.4  392.27  534.04397.8672   571.3  402.23   579.2  403.53
#Mann= 10 ,-1 , 0
       0     .12       0  199.07     .08       0   207.7    .045       0
   323.6     .12       0  345.35    .016       0  390.38     .12       0
  435.83    .016       0  447.38     .08       0  478.67    .016       0
  534.04     .06       0
Bank Sta=207.7,323.6
XS Rating Curve= 0 ,0
Exp/Cntr=0.3,0.1

Type RM Length L Ch R = 1 ,1697.3  ,167.6,173.2,176
XS GIS Cut Line= 2
      2416122.88      353928.794     2416553.509       354316.21
#Sta/Elev= 30
       0  394.07      20  392.33    47.9  391.36    75.9  388.17    87.9  388.14
   111.9  386.41   191.8  377.36   211.7  373.83   235.7  372.24   243.7  371.01
   255.7   367.3     262   366.7   267.6  365.43   271.6  365.47     277  366.52
   287.6  368.23   303.6   367.9  339.21369.3415   359.5  374.64   371.5   375.5
   387.2378.6967  414.41382.1938   423.4  384.11   435.4  388.28  454.71390.2065
   479.4  391.76   491.4  391.88   517.2394.2758   555.3  397.66   579.2  400.58
#Mann= 8 ,-1 , 0
       0     .12       0     262    .045       0     277     .12       0
  339.21    .016       0   387.2     .06       0  414.41     .12       0
  454.71     .08       0   517.2     .06       0
#XS Ineff= 2 , 0
                          286.07          370.95
Permanent Ineff=
       F       F
Bank Sta=262,277
XS Rating Curve= 0 ,0
Exp/Cntr=0.3,0.1