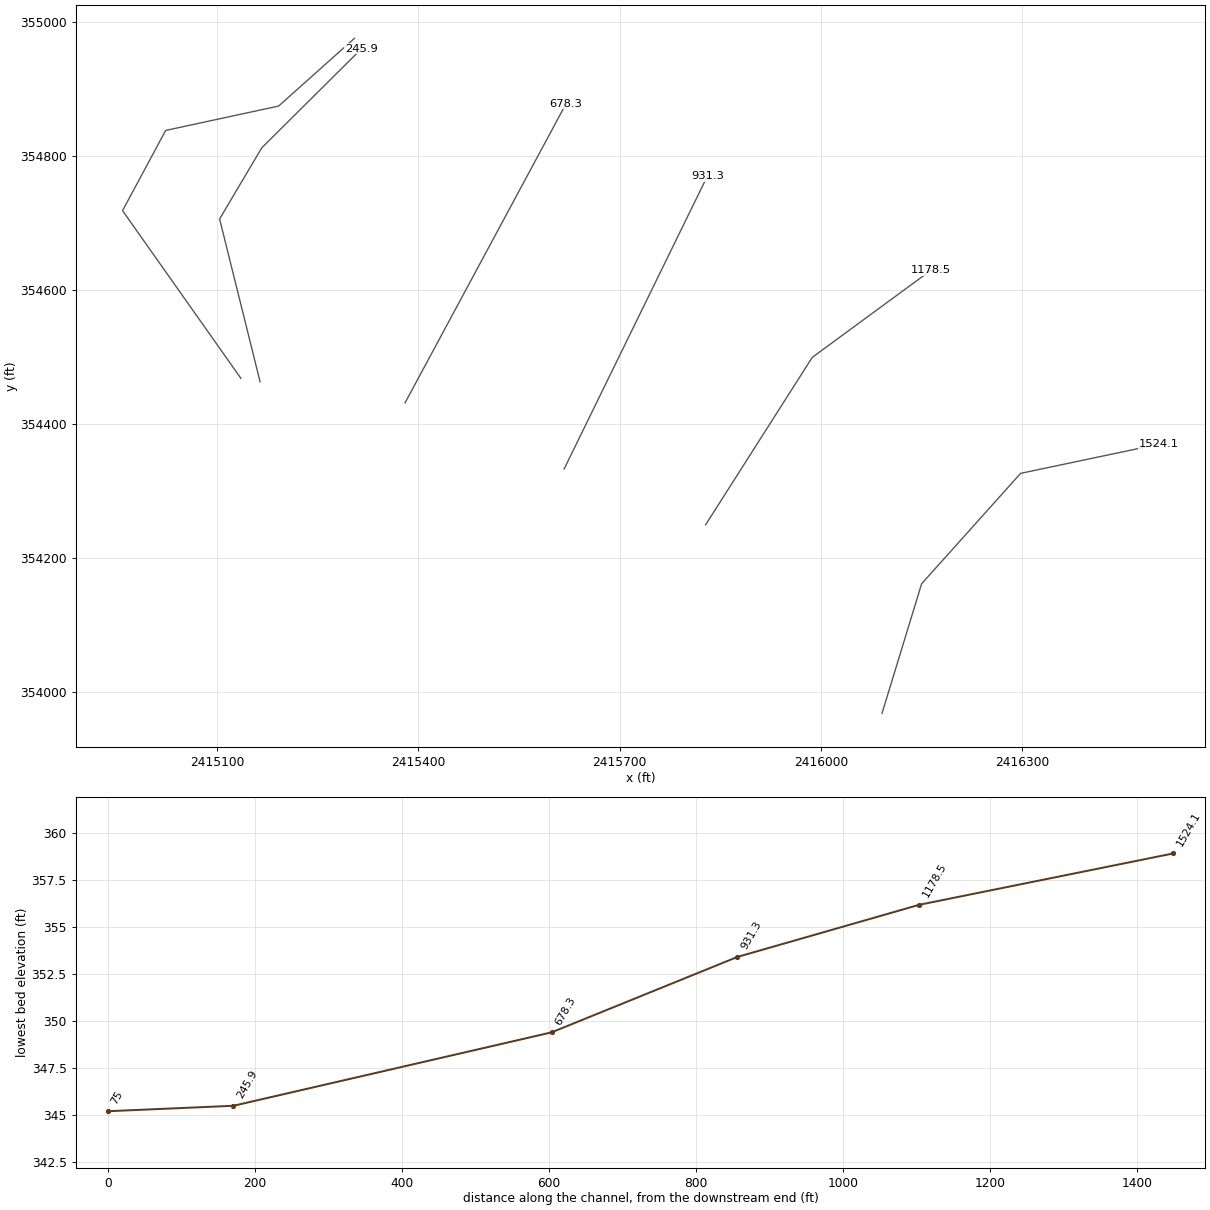
HEC-RAS study OPQNTRIB2.prj: OPQNTRIB2

--- OPQNTRIB2.g01 (geometry) --- (continued)

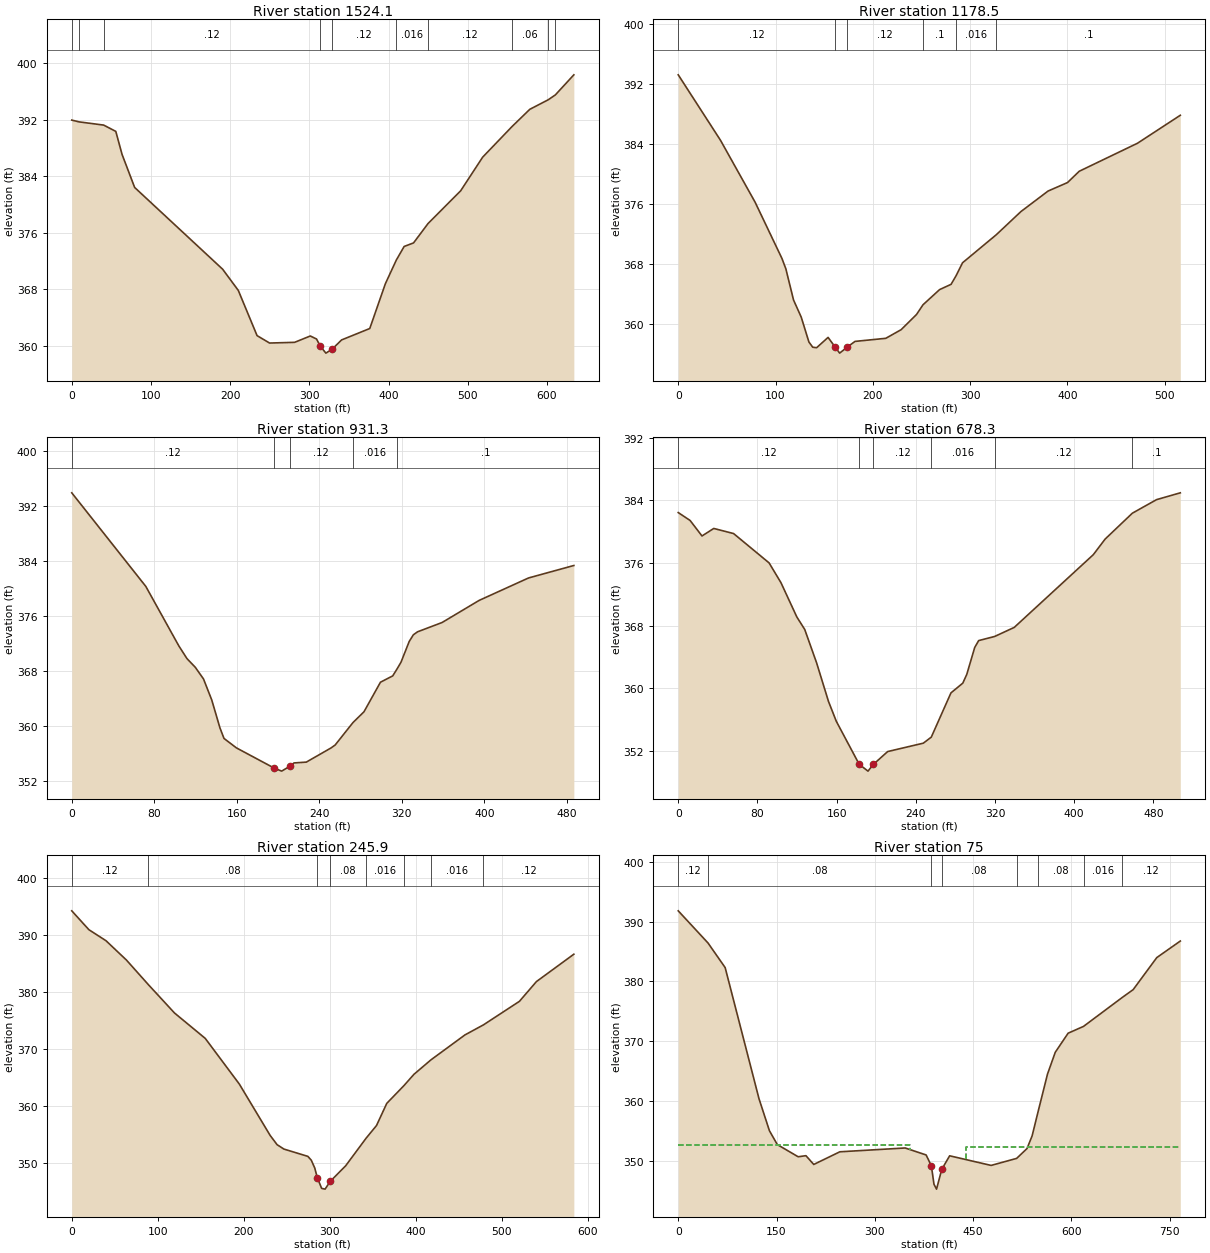
Type RM Length L Ch R = 1 ,1524.1  ,343.9,345.6,348.9
XS GIS Cut Line= 4
     2416090.915      353967.363     2416149.942      354160.939
     2416297.512       354325.87     2416503.241      354369.273
#Sta/Elev= 30
       0  391.96    9.19 391.709   40.31391.2518    55.6  390.36    63.5   387.1
    79.4  382.41   190.5  370.82   210.3  367.81     234   361.4   249.8  360.35
   281.4  360.45   301.2  361.35   309.1  360.92   313.7  359.92   320.9  358.92
   328.7  359.47   340.7  360.79   376.3  362.41     396  368.76  409.86372.1222
   419.7  374.04   431.6  374.55  449.86377.2891   491.1  381.94   518.9  386.71
  556.11391.0634   578.4  393.49  601.76394.8491  610.67395.5341     634  398.38
#Mann= 10 ,-1 , 0
       0     .12       0    9.19     .08       0   40.31     .12       0
   313.7    .045       0   328.7     .12       0  409.86    .016       0
  449.86     .12       0  556.11     .06       0  601.76     .12       0
  610.67     .06       0
Bank Sta=313.7,328.7
XS Rating Curve= 0 ,0
Exp/Cntr=0.3,0.1

Type RM Length L Ch R = 1 ,1178.5  ,244.5,247.2,249.5
XS GIS Cut Line= 3
     2415828.038      354249.047     2415986.893      354499.047
     2416163.976      354629.255
#Sta/Elev= 30
       0  393.21    43.4  384.51      79  376.27   106.6  368.78   110.6  367.41
   118.5  363.26   126.4  360.98   134.3  357.67   138.2  356.98   142.2  356.91
     154  358.28   161.6  356.94   165.9  356.19   173.8     357   181.7  357.75
   213.3  358.16   229.1  359.31   244.9  361.33  251.54362.6186   268.6  364.64
   280.4  365.34  285.55366.4824   292.2  368.21  326.88371.9382   352.2  375.02
   380.1  377.75   400.1  378.88   412.1  380.38     472  384.11     516  387.83
#Mann= 6 ,-1 , 0
       0     .12       0   161.6    .045       0   173.8     .12       0
  251.54      .1       0  285.55    .016       0  326.88      .1       0
Bank Sta=161.6,173.8
XS Rating Curve= 0 ,0
Exp/Cntr=0.3,0.1

Type RM Length L Ch R = 1 ,931.3   ,253.9,252.9,252
XS GIS Cut Line= 2
     2415617.101       354332.38     2415830.643       354769.88
#Sta/Elev= 30
       0  393.86    71.8  380.26   103.8  371.62   111.7  369.77   119.7  368.52
   127.7  366.82   135.7  363.77   143.7  359.69   147.6  358.17   159.6   356.8
   196.3  353.86   203.5  353.42   211.3  354.12   215.5  354.61   227.4  354.73
   251.4  356.79   255.4  357.22  272.62360.4708   283.3  362.04   299.3  366.34
   311.2  367.26   315.7368.3475   319.2  369.24   327.2  372.27   331.2  373.23
   335.2  373.66   359.1  375.02     395  378.23   442.9  381.49   486.8   383.3
#Mann= 5 ,-1 , 0
       0     .12       0   196.3    .045       0   211.3     .12       0
  272.62    .016       0   315.7      .1       0
Bank Sta=196.3,211.3
XS Rating Curve= 0 ,0
Exp/Cntr=0.3,0.1

Type RM Length L Ch R = 1 ,678.3   ,407.4,432.5,409.1
XS GIS Cut Line= 2
     2415380.122      354431.339     2415620.086      354878.138
#Sta/Elev= 30
       0  382.43      12  381.42      24  379.44    35.9   380.4    55.9  379.75
    91.8     376   103.8  373.47   119.8   369.1   127.8   367.5   139.8  363.23
   151.8  358.31   159.7  355.77  182.86 350.272   191.7  349.41  197.22350.2838
   211.6  351.91   247.6  352.98  255.65353.7537   275.5   359.4   287.5  360.65
   291.5  361.77   299.5   365.2   303.5  366.08  319.69366.6086   339.4  367.76
   419.3  377.05   431.3  379.05  458.75382.3482   483.2  384.08   507.2  384.95
#Mann= 6 ,-1 , 0
       0     .12       0  182.86    .045       0  197.22     .12       0
  255.65    .016       0  319.69     .12       0  458.75      .1       0
Bank Sta=182.86,197.22
XS Rating Curve= 0 ,0
Exp/Cntr=0.3,0.1

Type RM Length L Ch R = 1 ,245.9   ,153.1,170.9,174.8
XS GIS Cut Line= 4
     2415163.976      354462.589     2415103.602      354705.835
     2415166.536      354812.172     2415315.018      354959.985
#Sta/Elev= 30
       0   394.2    19.9   390.9    39.8  388.97    63.6  385.58   89.08381.2816
   119.4  376.33   155.2  371.88   194.9  363.87   230.7  354.89   238.7  353.29
   246.6  352.52   274.5  351.24   278.5  350.56   282.5   349.2   285.5  347.49
   290.5  345.64   294.5  345.51   300.5  346.87   318.4  349.59  342.19354.4185
   354.3  356.64   366.2  360.51  386.14363.6128   397.9  365.61  417.73 368.144
   457.2   372.5  478.61374.2473   520.4  378.36   540.2  381.82   583.7  386.61
#Mann= 8 ,-1 , 0
       0     .12       0   89.08     .08       0   285.5    .045       0
   300.5     .08       0  342.19    .016       0  386.14     .08       0
  417.73    .016       0  478.61     .12       0
Bank Sta=285.5,300.5
XS Rating Curve= 0 ,0
Exp/Cntr=0.3,0.1

Type RM Length L Ch R = 1 ,75      ,74.9,75,74.9
XS GIS Cut Line= 5
      2415135.33      354467.797      2414958.97      354718.231
     2415023.206      354838.023     2415191.609      354874.481
     2415304.601       354975.61
#Sta/Elev= 30
       0  391.82   45.42386.4371    71.6  382.32   123.3  360.34   139.2  354.99
   151.2  352.68     183  350.64   194.9  350.82   206.8  349.35   246.6  351.47
   346.3  352.11   378.3  350.94   386.3  349.12   390.3  346.03   394.2  345.22
   402.2  348.54   414.2   350.8   477.5  349.19  516.44350.3663   532.3  352.02
   540.1  354.15  549.72358.4403   563.6  364.51   575.4  368.14     595  371.33
  618.47372.4674     677 377.264   694.3  378.63   730.3  383.99   766.2  386.76
#Mann= 8 ,-1 , 0
       0     .12       0   45.42     .08       0   386.3    .045       0
   402.2     .08       0  516.44    .016       0  549.72     .08       0
  618.47    .016       0     677     .12       0
#XS Ineff= 2 , 0
          353.35  352.67  438.39          352.26
Permanent Ineff=
       F       F
Bank Sta=386.3,402.2
XS Rating Curve= 0 ,0
Exp/Cntr=0.3,0.1

Chan Stop Cuts=-1
Use User Specified Reach Order=0
Composite Channel Slope=5